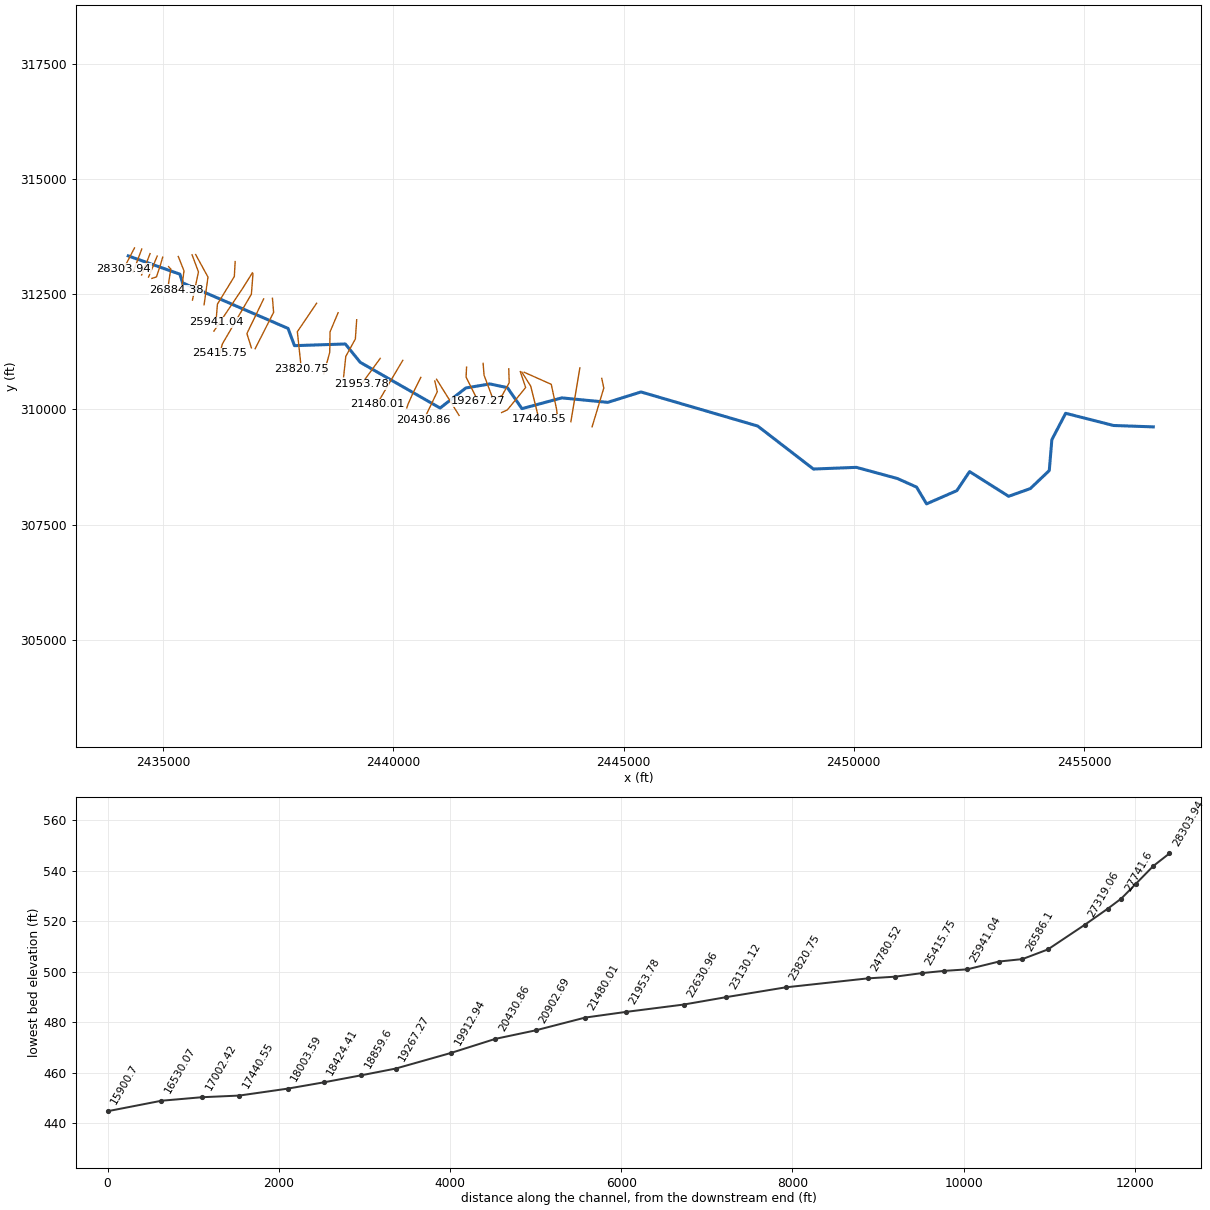
--- ElksRun.prj (project) ---

Proj Title=ElksRun
Current Plan=p05
Default Exp/Contr=0.3,0.1
English Units
Geom File=g04
Flow File=f03
Plan File=p05
Y Axis Title=Elevation
X Axis Title(PF)=Main Channel Distance
X Axis Title(XS)=Station
BEGIN DESCRIPTION:
END DESCRIPTION:
DSS Export Rating Curves= 0
DSS Export Rating Curve Sorted= 0
DSS Export Volume Flow Curves= 0
DXF OffsetX= 0
DXF OffsetY= 0
DXF ScaleX= 1
DXF ScaleY= 10

--- ElksRun.p05 (plan) ---

Plan Title=Plan 05
Program Version=4.10
Short Identifier=Final
Geom File=g04
Flow File=f03
Subcritical Flow
K Sum by GR= 0
Std Step Tol= 0.01
Critical Tol= 0.01
Num of Std Step Trials= 20
Max Error Tol= 0.3
Flow Tol Ratio= 0.001
Split Flow NTrial= 30
Split Flow Tol= 0.02
Split Flow Ratio= 0.02
Log Output Level= 0
Friction Slope Method= 1
Unsteady Friction Slope Method= 2
Unsteady Bridges Friction Slope Method= 1
Parabolic Critical Depth
Global Vel Dist= 0 , 0 , 0
Global Log Level= 0
CheckData=True
Encroach Param=-1 ,0,0, 0
Computation Interval=1HOUR
Output Interval=1HOUR
Run HTab= 0
Run UNet= 0
Run PostProcess= 0
Run WQNet= 0
UNET Theta= 1
UNET Theta Warmup= 1
UNET ZTol= 0.02
UNET ZSATol= 0.05
UNET MxIter= 20
UNET MaxInSteps= 0
UNET DtIC= 0
UNET DtMin= 0
UNET MaxCRTS= 20
UNET WFStab= 2
UNET SFStab= 1
UNET WFX= 1
UNET SFX= 1
UNET DSS MLevel= 4
UNET DZMax Abort= 100
UNET Convert EG Bridges= 0
UNET Use Existing IB Tables=-1
UNET Froude Reduction=False
UNET Froude Limit= 1
UNET Froude Power= 10
UNET Time Slicing=0,0, 5
UNET Junction Losses=0
Instantaneous Interval=1HOUR
Write IC File= 0
Write IC File at Sim End=0
Echo Input=False
Echo Parameters=False
Echo Output=False
Write Detailed= 0
WQ AD Non Conservative
WQ ULTIMATE=-1
WQ Max Comp Step=1HOUR
WQ Output Interval=15MIN
WQ Output Selected Increments= 0
WQ Output face flow=0
WQ Output face velocity=0
WQ Output face area=0
WQ Output face dispersion=0
WQ Output cell volume=0
WQ Output cell surface area=0
WQ Output cell continuity=0
WQ Output cumulative cell continuity=0
WQ Output face conc=0
WQ Output face dconc_dx=0
WQ Output face courant=0
WQ Output face peclet=0
WQ Output face adv mass=0
WQ Output face disp mass=0
WQ Output cell mass=0
WQ Output cell source sink temp=0
WQ Output cell source sink nsm=0
WQ Output MaxMinRange=-1
WQ Daily Max Min Mean=-1
WQ Daily Range=0
WQ Daily Time=0
WQ Create Restart=0
WQ Fixed Restart=0
WQ System Summary=0
WQ Use Fixed Temperature=0
Sorting and Armoring Iterations= 10
XS Update Threshold= 0.02
Hydraulics Update Threshold= 0.02
Energy Slope Method= 1
Volume Change Method= 0
XS Weighting Method= 0
Number of US Weighted Cross Sections= 1
Number of DS Weighted Cross Sections= 1
Upstream XS Weight=0.25
Main XS Weight=0.5
Downstream XS Weight=0.25
Number of DS XS's Weighted with US Boundary= 1
Upstream Boundary Weight= 1
Weight of XSs Associated with US Boundary= 0
Number of US XS's Weighted with DS Boundary= 1
Downstream Boundary Weight= 0.5
Weight of XSs Associated with DS Boundary= 0.5
Sediment Output Level= 4
Mass or Volume Output= 0
Output Increment Type= 1
Profile and TS Output Increment= 10
XS Output Flag= 0
XS Output Increment= 10
Disregard all LS=0
Disregard all Conn=0
Disregard all Breaches=0
Disregard all Pumps=0

--- ElksRun.f03 (steady flow) ---

Flow Title=FinalFlow
Program Version=4.10
Number of Profiles= 1
Profile Names=PF 1
River Rch & RM=ElksRun,Reach1          ,28303.94
     776
River Rch & RM=ElksRun,Reach1          ,10407.17
    1732
Boundary for River Rch & Prof#=ElksRun,Reach1          , 1
Up Type= 0
Dn Type= 3
Dn Slope=0.0025
DSS Import GetInterval= 0
DSS Import GetPeak= 0
DSS Import FillOption= 0

--- ElksRun.g04 (geometry) ---

Geom Title=FinalElksRun_Geo
Program Version=4.10

River Reach=ElksRun         ,Reach1
Reach XY= 30
2434238.74791153313336.0815848562435360.69218995312939.275948018
2435419.02540661312750.3868900982437710.44011511 311760.73565419
2437850.00414044311386.1704584362438954.58099952311422.748141184
2439279.00193861311023.7948708532441014.15266778310030.687277019
2441572.31493728310466.6719693542442095.79912652310554.549090192
2442475.74849786310474.0259572712442791.35088502310017.704035267
2443658.12441394310251.5142631832444656.05122386310154.660454273
2445377.96743095310380.4011445192447912.61229603309640.342257187
2449124.46814002308705.6305439322450056.15623727308742.482176274
2450948.91363811308499.6385018532451364.58242619308313.584412023
2451581.62989236307948.9411124442452240.42581886 308236.66822727
2452516.81404561308650.1637913582453364.97147003 308113.45095402
2453836.10701069308281.1737156812454247.90179077308672.936383605
2454304.12444736 309343.165686192454603.66289027309916.824971944
2455643.54401261309651.9646092652456507.86544669309621.663488775

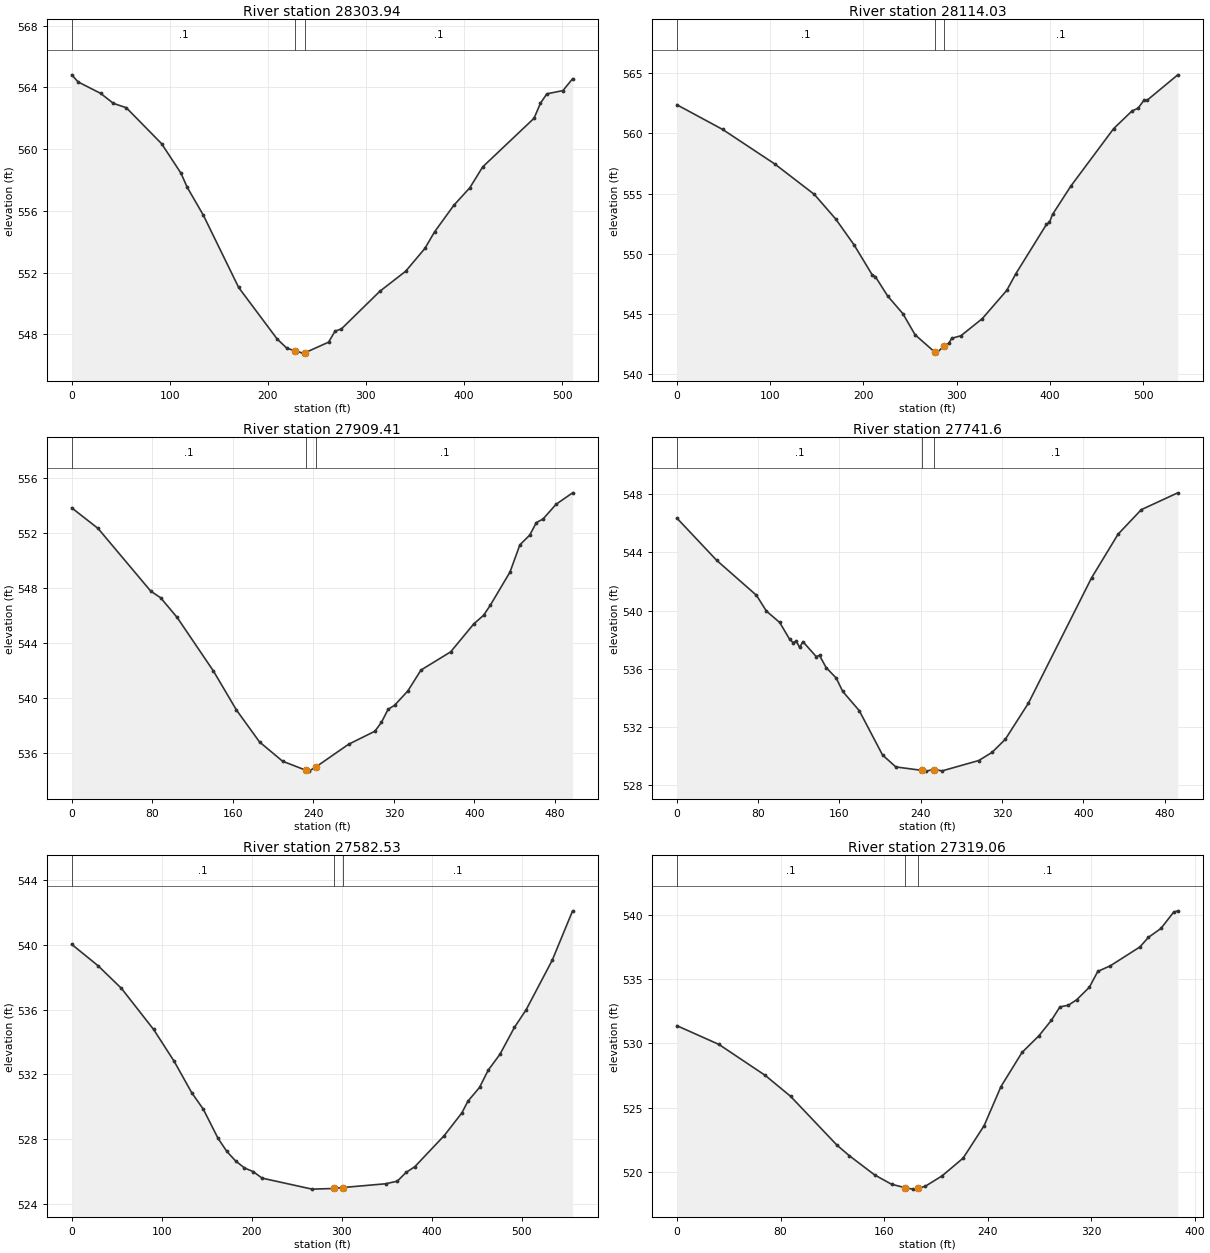
Type RM Length L Ch R = 1 ,28303.94,185.75,189.91,192.84
Node Name=964
XS GIS Cut Line= 2
2434374.93103811 313511.46542044 2434139.4495537313058.207796767
#Sta/Elev= 30
       0  564.81    6.55  564.35   29.47  563.61   42.56  562.96   55.66  562.68
   91.68  560.35  111.32  558.45  117.87  557.52  134.24  555.72  170.26  551.04
  209.55   547.7  219.37  547.11   227.7  546.94  235.74  546.79   237.7  546.81
  261.94   547.5  268.49  548.21  275.03  548.36  314.32   550.8  340.52  552.09
  360.16  553.57  369.99  554.64  389.63  556.36     406   557.5   419.1  558.85
  471.49     562  478.04  562.98  484.58  563.58  500.96  563.79  510.78  564.56
#Mann= 3 , 0 , 0
       0      .1       0   227.7    .045       0   237.7      .1       0
Bank Sta=227.7,237.7
XS Rating Curve= 0 ,0
Exp/Cntr=0.3,0.1

Type RM Length L Ch R = 1 ,28114.03,204.13,204.62,202.32
XS GIS Cut Line= 2
2434532.86313695313486.323738441 2434343.0613512312983.845084608
#Sta/Elev= 30
       0  562.36   49.13  560.31  104.81  557.46  147.38  554.93  170.31  552.89
  189.96  550.75  209.61  548.24  212.89  548.11  225.99  546.51  242.36  545.04
  255.46  543.29  276.51  541.86  278.39  541.77  286.69  542.38  291.49  542.57
  294.77     543  304.59  543.21  327.52  544.63  353.72  546.97  363.55  548.36
   396.3  552.44  399.57  552.62  402.85  553.27   422.5  555.62  468.35  560.38
     488  561.84  494.55  562.07   501.1  562.76  504.38  562.74  537.13  564.84
#Mann= 3 , 0 , 0
       0      .1       0  276.51    .045       0  286.69      .1       0
Bank Sta=276.51,286.69
XS Rating Curve= 0 ,0
Exp/Cntr=0.3,0.1

Type RM Length L Ch R = 1 ,27909.41,166.3,167.81,169
XS GIS Cut Line= 2
2434712.61080894313385.4607511912434529.29621494312923.034510687
#Sta/Elev= 30
       0  553.83   26.18  552.33   78.54  547.77   88.36  547.29  104.72  545.86
  140.72  541.97  163.63  539.13  186.54  536.81  209.45  535.41  232.71  534.75
  235.63  534.69  242.61     535   274.9  536.64  301.08  537.59  307.62  538.24
  314.17  539.18  320.71  539.48  333.81  540.52   346.9  542.04  376.35  543.36
  399.26  545.39  409.08  546.02  415.62  546.74  435.26  549.16  445.07  551.14
  454.89  551.85  461.44  552.76  467.98  553.01  481.07  554.09  497.44  554.92
#Mann= 3 , 0 , 0
       0      .1       0  232.71    .045       0  242.61      .1       0
Bank Sta=232.71,242.61
XS Rating Curve= 0 ,0
Exp/Cntr=0.3,0.1

Type RM Length L Ch R = 1 ,27741.6 ,157.79,159.07,159.51
XS GIS Cut Line= 2
2434867.49468553313333.1724699442434679.81756744312877.259011686
#Sta/Elev= 30
       0  546.37   39.18  543.46   78.36  541.05   88.16  539.96  101.22  539.18
  111.01  538.02  114.28   537.8  117.54   537.9  120.81  537.46  124.07  537.86
  137.13  536.83   140.4  536.91  146.93  536.07  156.73  535.36  163.26  534.43
  179.58   533.1  202.44  530.05   215.5  529.23  241.33  528.99  244.88  528.94
  252.82  529.05  261.21  528.96  297.12  529.67  310.19  530.23  323.25  531.13
   346.1  533.63  408.14  542.25  434.26  545.26  457.11  546.95  493.03  548.11
#Mann= 3 , 0 , 0
       0      .1       0  241.33    .045       0  252.82      .1       0
Bank Sta=241.33,252.82
XS Rating Curve= 0 ,0
Exp/Cntr=0.3,0.1

Type RM Length L Ch R = 1 ,27582.53,258.2,263.47,268.01
XS GIS Cut Line= 4
2434987.00592944 313309.269958692434940.97190078313149.921524107
2434852.44484685312879.9145181922434750.81545694312847.375213191
#Sta/Elev= 30
       0  540.03   29.27  538.71   55.29  537.31   91.06  534.77  113.83  532.81
  133.34  530.87  146.35  529.84  162.61  528.05   172.4  527.24   182.2  526.65
  191.99  526.22  201.79  525.99  211.59  525.59  267.11  524.91  291.52  524.95
  301.54  525.01  348.77  525.24  361.83   525.4  371.63  525.94  381.43   526.3
  414.09  528.22  433.68  529.62  440.22  530.33  453.25  531.19  462.95  532.26
  475.88  533.23  492.05   534.9  504.99  535.98  534.09  539.05  556.73   542.1
#Mann= 3 , 0 , 0
       0      .1       0  291.52    .045       0  301.54      .1       0
Bank Sta=291.52,301.54
XS Rating Curve= 0 ,0
Exp/Cntr=0.3,0.1

Type RM Length L Ch R = 1 ,27319.06,424.09,434.68,433.45
XS GIS Cut Line= 3
2435113.46893111 313103.026932852435163.00524935313051.468965098
2435114.47975586312740.099181026
#Sta/Elev= 30
       0  531.37    32.5  529.91   68.25   527.5   87.74  525.88  123.48  522.09
  133.22  521.25  152.72  519.76  165.71  519.04  176.23  518.77  181.96  518.66
  186.13  518.72   191.7  518.88   204.7  519.69  220.94  521.07  237.18   523.6
  250.18  526.64  266.42  529.29  279.42  530.58  289.16   531.8  295.66  532.83
  302.16  532.96  308.66  533.39   318.4  534.36   324.9  535.59  334.65  536.03
  357.39  537.49  363.89  538.23  373.63  538.93  383.38  540.19  386.63   540.3
#Mann= 3 , 0 , 0
       0      .1       0  176.23    .045       0  186.13      .1       0
Bank Sta=176.23,186.13
XS Rating Curve= 0 ,0
Exp/Cntr=0.3,0.1

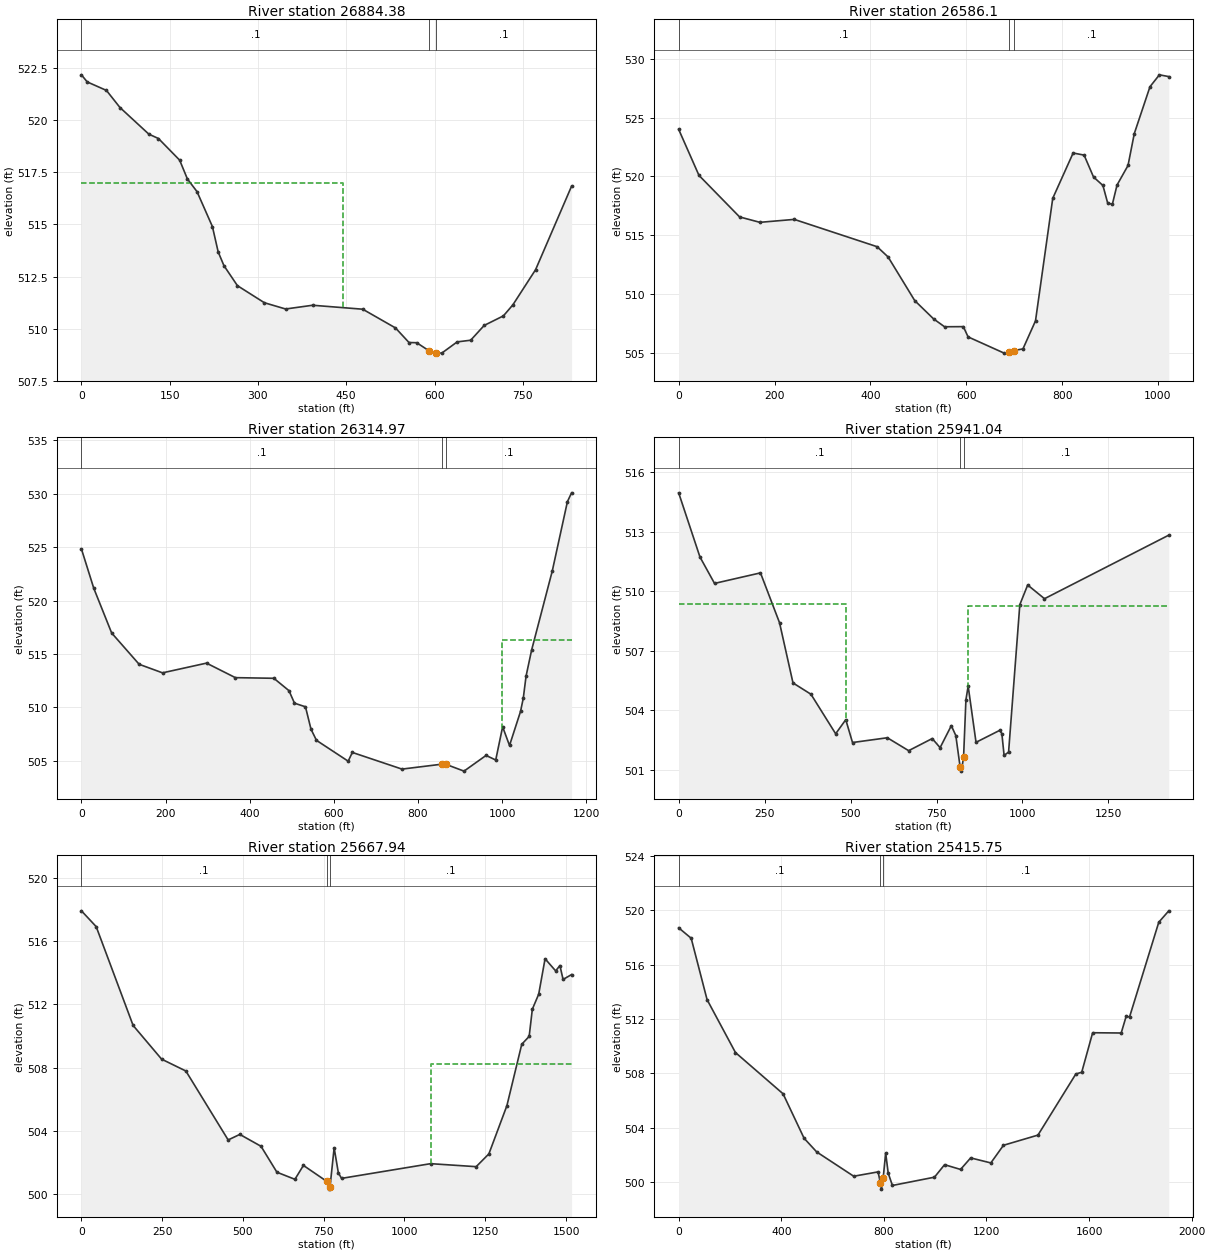
Type RM Length L Ch R = 1 ,26884.38,306.96,298.28,294.84
XS GIS Cut Line= 4
2435325.76673485313323.4123188562435450.11261478 313010.02055718
2435397.54349419312636.9829174432435288.27894895312589.775990859
#Sta/Elev= 30
       0  522.19    9.82  521.85   42.55  521.44   65.47  520.62  114.57  519.34
  130.94  519.13  166.94  518.09  180.04  517.19   196.4  516.58  222.59   514.9
  232.41  513.68  242.23  513.02  265.14  512.06  310.97  511.24  346.99  510.94
  392.85  511.12  478.02  510.93  533.71  510.03  556.64  509.33  569.75  509.32
  591.36  508.92  601.78  508.83  612.33  508.82  638.54  509.36  661.47  509.44
   684.4  510.15   717.1  510.61  733.18  511.14  771.79  512.83  832.91  516.84
#Mann= 3 , 0 , 0
       0      .1       0  591.36    .045       0  601.78      .1       0
#XS Ineff= 2 , 0
          443.94  516.98
Permanent Ineff=
       F       F
Bank Sta=591.36,601.78
XS Rating Curve= 0 ,0
Exp/Cntr=0.3,0.1

Type RM Length L Ch R = 1 ,26586.1 ,266.62,271.13,271.41
XS GIS Cut Line= 3
2435624.85045427313360.9398028552435764.09262986312988.421190932
2435633.89210285312377.201284766
#Sta/Elev= 30
       0     524   42.38  520.09  127.13  516.56  169.51   516.1  241.22  516.35
  414.05  514.03  436.95  513.16  492.58  509.45  531.84   507.9  554.74  507.23
     594  507.24  603.82  506.37  679.07  504.99  689.66  505.05  699.74  505.21
  718.34  505.35  744.51  507.73   780.5  518.14  823.04  521.99  845.94  521.81
  865.57  519.95   885.2  519.23  895.02  517.75  904.83  517.63  914.65  519.27
  937.55  520.93  950.64  523.64  983.36  527.62 1002.99  528.63 1022.62  528.48
#Mann= 3 , 0 , 0
       0      .1       0  689.66    .045       0  699.74      .1       0
Bank Sta=689.66,699.74
XS Rating Curve= 0 ,0
Exp/Cntr=0.3,0.1

Type RM Length L Ch R = 1 ,26314.97,386.22,373.92,361.59
XS GIS Cut Line= 3
2435702.60915703 313366.36466077 2435970.9672161312876.303961098
2435885.97493203312275.934098855
#Sta/Elev= 30
       0  524.84   29.41  521.15   71.88  516.97  137.23  514.04  192.78  513.24
  297.33  514.15  365.95  512.79  457.44  512.73  493.38  511.57  506.45   510.4
  532.59  510.06  545.66  507.97  558.73  506.92  634.11  504.97  643.94  505.79
  761.94  504.23  856.72  504.69  866.79  504.67  909.43  504.04  961.87  505.51
  984.81  505.08  1001.2  508.19 1017.59  506.44 1043.81  509.63 1050.37  510.88
 1056.92  512.93 1070.03  515.36  1119.2  522.77 1155.25  529.27 1165.08  530.09
#Mann= 3 , 0 , 0
       0      .1       0  856.72    .045       0  866.79      .1       0
#XS Ineff= 2 , 0
                          999.89          516.36
Permanent Ineff=
       F       F
Bank Sta=856.72,866.79
XS Rating Curve= 0 ,0
Exp/Cntr=0.3,0.1

Type RM Length L Ch R = 1 ,25941.04,274.32,273.1,271.83
XS GIS Cut Line= 4
2436561.21013011313213.0171984432436543.12683295312887.515552849
2436176.03307894312288.9540859312436143.48294719311892.926990852
#Sta/Elev= 30
       0  514.95   61.94  511.72  104.32  510.39  237.98  510.92   293.4  508.41
  332.54  505.38  384.79  504.81  456.64  502.82  486.03  503.53  505.63  502.38
  606.87  502.62  668.92  501.97   737.5  502.58  760.36  502.12  793.02  503.23
  806.09  502.73   818.7  501.14  822.42  500.94  828.68  501.65  835.48  504.53
  842.01  505.22  864.87  502.39  933.46  502.99  939.99  502.83  946.52  501.73
  959.58   501.9  992.24  509.32  1015.1  510.31 1063.99  509.62 1425.53  512.82
#Mann= 3 , 0 , 0
       0      .1       0   818.7    .045       0  828.68      .1       0
#XS Ineff= 2 , 0
          486.76  509.34  842.82          509.26
Permanent Ineff=
       F       F
Bank Sta=818.7,828.68
XS Rating Curve= 0 ,0
Exp/Cntr=0.3,0.1

Type RM Length L Ch R = 1 ,25667.94,249.94,252.19,253.8
XS GIS Cut Line= 3
2436935.53713736312968.8910462712436722.15272161312628.561018273
2436100.08277152311702.689182356
#Sta/Elev= 30
       0  517.92   45.72  516.92  160.02  510.67   248.2  508.54  323.31  507.79
  454.18  503.43  490.27  503.78  555.89  503.03   605.1  501.39  660.87  500.94
  687.11  501.82  759.49  500.81  765.85  500.32  769.51  500.47  782.25  502.93
  795.38  501.34  805.22     501  1080.8  501.93 1221.87  501.74 1261.24  502.55
 1317.01   505.6 1362.94  509.48 1385.91  509.98 1395.75   511.7 1415.43  512.65
 1435.12  514.89 1467.93  514.12 1481.05  514.46 1490.89  513.58 1517.14  513.89
#Mann= 3 , 0 , 0
       0      .1       0  759.49    .045       0  769.51      .1       0
#XS Ineff= 2 , 0
                         1080.79          508.25
Permanent Ineff=
       F       F
Bank Sta=759.49,769.51
XS Rating Curve= 0 ,0
Exp/Cntr=0.3,0.1

Type RM Length L Ch R = 1 ,25415.75,311.34,316.12,317.21
Node Name=970
XS GIS Cut Line= 4
2436948.19557661 312947.190958442436913.83704953312505.593416438
2436284.53384618 311426.012898432436224.85844061311216.244945273
#Sta/Elev= 30
       0  518.72   48.85  517.95  110.73  513.43  221.47  509.53  407.11  506.49
  488.85  503.22  538.05  502.21  682.36  500.42  777.47  500.74  786.55   499.9
  790.59  499.47  797.42  500.31  806.99  502.13  816.83  500.65  833.23  499.74
  997.22  500.35 1036.58  501.27 1098.89  500.92 1138.25  501.77 1216.97   501.4
 1266.16   502.7 1400.63  503.45 1548.23  507.95 1571.18  508.08 1613.82  510.99
 1725.09  510.97 1744.62  512.21 1757.64  512.15 1871.57  519.13 1910.63  519.97
#Mann= 3 , 0 , 0
       0      .1       0  786.55    .045       0  797.42      .1       0
Bank Sta=786.55,797.42
XS Rating Curve= 0 ,0
Exp/Cntr=0.3,0.1

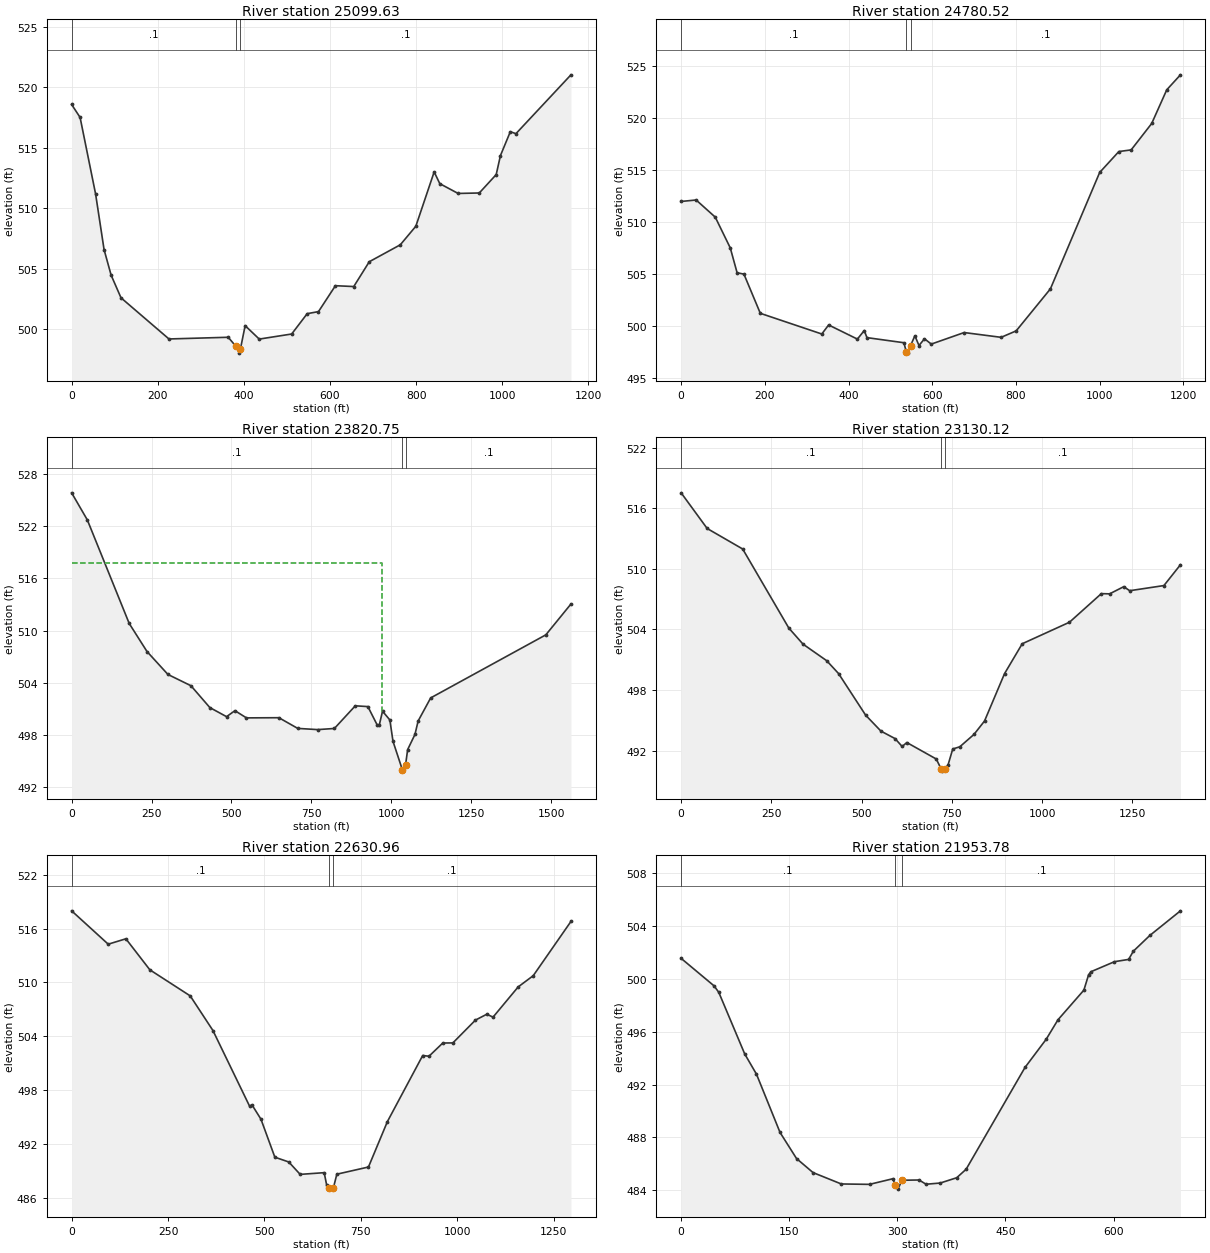
Type RM Length L Ch R = 1 ,25099.63,319.78,319.11,318.04
XS GIS Cut Line= 3
2437179.66361761312400.7097679382436816.18665427311648.438962772
2436913.83704953311339.212547109
#Sta/Elev= 30
       0  518.58   19.66  517.51    55.7  511.18   75.36  506.59   91.74  504.48
  114.67  502.61  226.07  499.21  363.68  499.35  381.37  498.61  389.89  498.04
  392.11  498.39     403  500.31  435.76   499.2  511.12  499.62  547.16   501.3
  573.37  501.47  612.69  503.61  655.28  503.54  691.32  505.59   763.4  506.99
  799.44  508.52  842.03  513.01  855.13  512.04  897.72  511.23  946.85  511.27
  986.16  512.79  995.98  514.36 1018.91  516.33 1032.01  516.17 1159.76  521.03
#Mann= 3 , 0 , 0
       0      .1       0  381.37    .045       0  392.11      .1       0
Bank Sta=381.37,392.11
XS Rating Curve= 0 ,0
Exp/Cntr=0.3,0.1

Type RM Length L Ch R = 1 ,24780.52,939.09,959.77,974.22
XS GIS Cut Line= 3
2437371.34794553312415.1762744342437396.66482402312109.566321358
2436995.21254294311319.320526525
#Sta/Elev= 30
       0  511.96   35.89   512.1   81.56  510.45  117.44  507.49  133.75   505.1
  150.07  504.97  189.21   501.2  336.09  499.21  352.45  500.08  421.13  498.72
  437.49  499.54  444.03  498.86  532.34  498.37  538.24  497.45  542.15  497.37
  548.27   498.1   558.5  499.04  568.32   498.1   581.4  498.75  597.75  498.24
  676.25  499.35  764.56  498.89  800.54  499.51  882.31  503.55 1000.06  514.75
 1045.85  516.76 1075.28  516.92 1124.34  519.46 1160.32   522.7 1193.03  524.14
#Mann= 3 , 0 , 0
       0      .1       0  538.24    .045       0  548.27      .1       0
Bank Sta=538.24,548.27
XS Rating Curve= 0 ,0
Exp/Cntr=0.3,0.1

Type RM Length L Ch R = 1 ,23820.75,692.58,690.62,684.71
XS GIS Cut Line= 3
2438330.52417678312307.2483406812437912.07816328 311688.94741194
 2437999.5146682 310878.28630361
#Sta/Elev= 30
       0  525.86   49.12  522.74   180.1  510.82  235.76  507.59  301.25  504.95
  373.29  503.65  432.24  501.14  484.63  500.09  510.82  500.78  546.84  499.95
  648.35  499.97  707.29  498.74  769.51   498.6   821.9  498.73  887.39  501.34
  926.69  501.25  956.16  499.11  962.71  499.18  972.53  500.72  995.45  499.71
 1005.28  497.25 1034.64  493.97 1038.02  493.82 1044.65  494.56 1051.12   496.3
 1074.04  498.05 1083.87  499.59 1123.16  502.25 1483.36  509.51 1561.95  513.06
#Mann= 3 , 0 , 0
       0      .1       0 1034.64    .045       0 1044.65      .1       0
#XS Ineff= 2 , 0
          971.72  517.75
Permanent Ineff=
       F       F
Bank Sta=1034.64,1044.65
XS Rating Curve= 0 ,0
Exp/Cntr=0.3,0.1

Type RM Length L Ch R = 1 ,23130.12,509.45,499.16,479.83
XS GIS Cut Line= 4
 2438797.7686491312100.8865486832438622.72109894311687.137704268
2438615.48784569311240.4768521932438487.09538594310770.307845026
#Sta/Elev= 30
       0  517.52   72.14  513.99  170.52  511.96  298.41  504.13  337.76  502.54
  403.35   500.9  436.14  499.63  511.21  495.51   553.6  493.93  592.73  493.19
  612.29  492.41  625.33   492.8  706.85  491.17  720.92  490.15  723.16  489.97
  731.79  490.21  739.46  490.58   752.5  492.16  772.07  492.38   811.2   493.6
  840.54  494.93  895.98  499.62  945.04  502.58 1075.88  504.71  1164.2  507.54
  1187.1  507.52 1226.35  508.23 1242.71  507.83 1337.57  508.34 1383.36   510.4
#Mann= 3 , 0 , 0
       0      .1       0  720.92    .045       0  731.79      .1       0
Bank Sta=720.92,731.79
XS Rating Curve= 0 ,0
Exp/Cntr=0.3,0.1

Type RM Length L Ch R = 1 ,22630.96,680,677.18,670.96
XS GIS Cut Line= 4
2439201.39087336311949.3471536042439172.45720419311531.619970679
2438964.49797444311151.8681055162438917.43966961310711.330928847
#Sta/Elev= 30
       0  517.97   94.87  514.26  140.67  514.86  202.82  511.41   307.5  508.51
  366.39  504.66  461.37  496.25  467.93  496.37  490.89   494.8  526.97  490.57
  563.05  490.04  592.57  488.66  654.89  488.85  661.45  487.44  667.66  487.18
  674.57  487.02  678.74  487.16  687.69  488.68  769.69  489.48  818.89  494.54
  910.33  501.88  926.62   501.8  962.45  503.27  988.52  503.28 1047.15  505.82
 1076.47  506.47 1092.76  506.15 1157.91  509.51 1197.01  510.76 1294.74  516.79
#Mann= 3 , 0 , 0
       0      .1       0  667.66    .045       0  678.74      .1       0
Bank Sta=667.66,678.74
XS Rating Curve= 0 ,0
Exp/Cntr=0.3,0.1

Type RM Length L Ch R = 1 ,21953.78,470.36,473.77,476.04
Node Name=978
XS GIS Cut Line= 2
2439712.02075762311108.9521808482439303.98384403310548.942474097
#Sta/Elev= 30
       0  501.53   45.76  499.45   52.29  498.96   88.25  494.31  104.59  492.78
  137.27  488.38  160.15  486.41  183.03  485.35  222.25  484.49  261.47  484.46
  294.15  484.89  296.72   484.4  300.69   484.1  306.74  484.77  330.11  484.79
  339.91  484.47  359.52  484.56   382.4  484.96  395.47   485.6  477.18  493.29
   506.6  495.42  522.94  496.89  558.89  499.13  565.43  500.29   568.7  500.52
  601.38  501.28  620.99  501.45  627.53  502.07  650.41  503.26   692.9  505.12
#Mann= 3 , 0 , 0
       0      .1       0  296.72    .045       0  306.74      .1       0
Bank Sta=296.72,306.74
XS Rating Curve= 0 ,0
Exp/Cntr=0.3,0.1

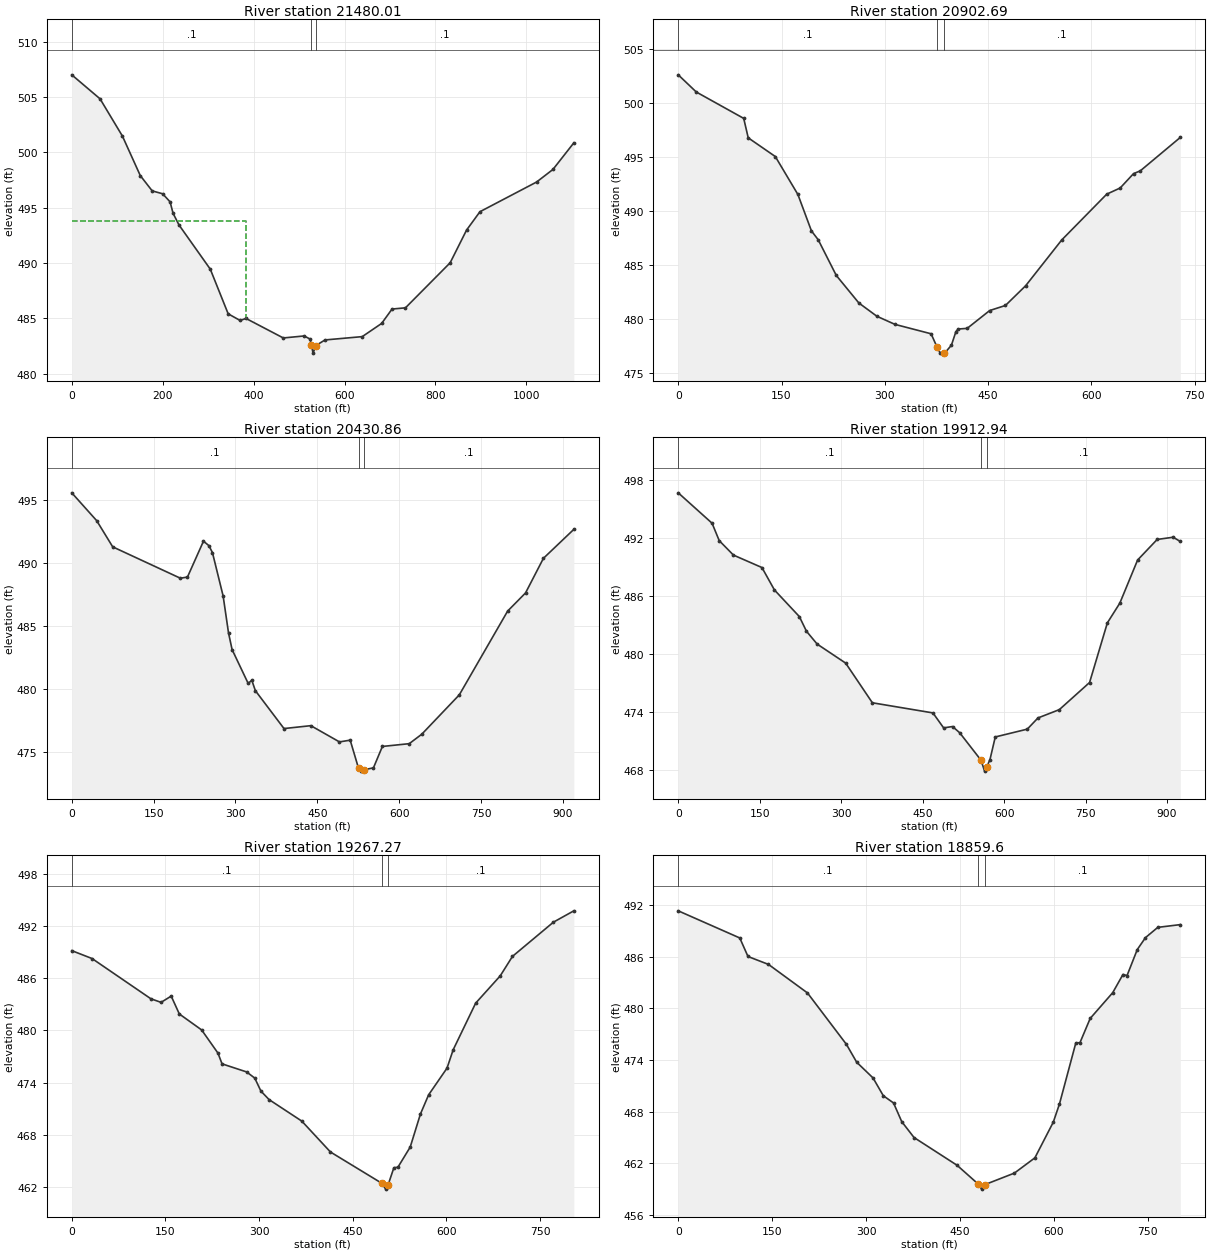
Type RM Length L Ch R = 1 ,21480.01,570.28,577.32,573.36
Node Name=979
XS GIS Cut Line= 3
2440203.16117953311068.2101363542439917.39370644310586.279997855
2439642.70724794310116.582118347
#Sta/Elev= 30
       0     507   62.25  504.83   111.4  501.47  150.72   497.9  176.93  496.52
  199.87  496.26  216.25  495.53   222.8   494.5  235.91  493.44  304.72  489.45
  344.03  485.42  370.25  484.82  383.35     485  465.27  483.24  511.14  483.42
  524.24  483.14  526.72  482.64   530.8  481.87  536.84  482.55  557.01  483.06
  638.95  483.36  681.57  484.55  704.51  485.85  734.01  485.96  832.35  490.03
   868.4  492.98   897.9  494.64 1022.46  497.32 1058.52  498.46 1104.41  500.86
#Mann= 3 , 0 , 0
       0      .1       0  526.72    .045       0  536.84      .1       0
#XS Ineff= 2 , 0
          382.65   493.8
Permanent Ineff=
       F       F
Bank Sta=526.72,536.84
XS Rating Curve= 0 ,0
Exp/Cntr=0.3,0.1

Type RM Length L Ch R = 1 ,20902.69,470.22,471.83,470.63
Node Name=980
XS GIS Cut Line= 4
2440594.29622403310696.7515616862440417.35464877310341.673203602
2440322.09729336310126.4174005242440290.35063769310034.732544526
#Sta/Elev= 30
       0  502.58   26.23  500.99   95.08  498.55  101.64  496.75  140.98  495.02
  173.77  491.51  193.44  488.14  203.28  487.32  229.51  484.02   262.3  481.47
  288.53  480.24  314.76  479.49  367.21  478.62  375.63  477.42  380.33  476.85
  385.66  476.84  386.89  476.83  396.72  477.56  403.26  478.82  406.53  479.06
  419.61  479.12   452.3  480.77  475.19  481.24  504.61  483.07  556.92   487.3
  622.31  491.54  641.82  492.11  661.22  493.44  670.92  493.69  729.14  496.79
#Mann= 3 , 0 , 0
       0      .1       0  375.63    .045       0  385.66      .1       0
Bank Sta=375.63,385.66
XS Rating Curve= 0 ,0
Exp/Cntr=0.3,0.1

Type RM Length L Ch R = 1 ,20430.86,469.35,517.92,538.65
Node Name=981
XS GIS Cut Line= 3
2440898.24213845310619.7241566932440952.36965486310384.478564188
2440658.83284035309772.423029765
#Sta/Elev= 30
       0  495.55   45.67  493.34   75.03  491.26  198.99  488.77  212.03  488.86
  241.39  491.71  251.23  491.36  257.79  490.81  277.46  487.35   287.3  484.42
  293.86   483.1  323.37  480.41  329.93  480.67  336.49  479.84  388.96  476.83
  438.15  477.06  490.62  475.77  510.29  475.91  525.62  473.67  529.97  473.45
  535.68  473.56  552.92  473.71  569.32  475.41  618.51  475.63  641.46  476.38
  710.32  479.51  798.86  486.16  831.66   487.6  864.45  490.35   920.2  492.65
#Mann= 3 , 0 , 0
       0      .1       0  525.62    .045       0  535.68      .1       0
Bank Sta=525.62,535.68
XS Rating Curve= 0 ,0
Exp/Cntr=0.3,0.1

Type RM Length L Ch R = 1 ,19912.94,631.57,645.67,625.27
Node Name=982
XS GIS Cut Line= 3
2440936.81456786310655.8641762732441242.57084611310166.334643513
 2441425.5763856309871.238448933
#Sta/Elev= 30
       0  496.72   62.31  493.57   75.43  491.77  101.66  490.27  154.13  488.98
  177.09  486.66     223   483.9  236.12  482.38  255.79  481.05  308.26  479.08
  357.45  474.97  468.95  473.92  488.63  472.37  505.02  472.51  518.14  471.87
  557.49  469.02  564.05  467.89  567.66   468.3  573.89  469.07  583.72  471.43
  642.69  472.24  662.34   473.4  701.65  474.26  757.34  477.07   790.1  483.25
  813.03  485.29  845.79  489.76  881.82  491.89   911.3  492.12  924.41  491.68
#Mann= 3 , 0 , 0
       0      .1       0  557.49    .045       0  567.66      .1       0
Bank Sta=557.49,567.66
XS Rating Curve= 0 ,0
Exp/Cntr=0.3,0.1

Type RM Length L Ch R = 1 ,19267.27,398.51,407.67,394.61
Node Name=983
XS GIS Cut Line= 3
2441588.41398644310920.4276235252441578.25094903310702.933635935
2441840.46335112310178.508175597
#Sta/Elev= 30
       0   489.2    32.5  488.29  126.74  483.65  142.99  483.24  159.24  483.96
  172.24   481.9  207.98  480.06  234.11  477.39  240.66  476.15  279.97  475.22
  293.07  474.51   302.9  473.01     316  472.03  368.41  469.55  414.27  465.99
  496.66  462.38  502.71  461.71  506.55  462.19  515.81  464.17  522.36  464.24
  542.01  466.56  558.39  470.37  571.49  472.58  600.97  475.66   610.8  477.77
  646.83  483.15  686.14  486.29  705.79  488.54   771.3  492.48  804.06  493.79
#Mann= 3 , 0 , 0
       0      .1       0  496.66    .045       0  506.55      .1       0
Bank Sta=496.66,506.55
XS Rating Curve= 0 ,0
Exp/Cntr=0.3,0.1

Type RM Length L Ch R = 1 ,18859.6 ,459,435.19,405.95
Node Name=984
XS GIS Cut Line= 3
2441948.19410677311002.1403865962441968.52083777310743.993265107
2442159.59033753310235.422431856
#Sta/Elev= 30
       0  491.31   98.33  488.16  111.45  486.01  144.22  485.09   206.5  481.78
  268.76  475.81  285.13  473.74  311.31  471.91  327.67  469.85  344.04  469.01
  357.13  466.84  376.77     465  445.49  461.78  478.67  459.64  484.77  459.01
  490.25  459.54  537.13  460.87  569.86  462.64  599.31  466.79  609.13  468.89
  635.32  475.99  641.86     476  658.22  478.82  694.22  481.81  710.59  483.92
  717.13   483.8   733.5  486.82  746.59   488.2  766.23  489.39  802.23  489.71
#Mann= 3 , 0 , 0
       0      .1       0  478.67    .045       0  490.25      .1       0
Bank Sta=478.67,490.25
XS Rating Curve= 0 ,0
Exp/Cntr=0.3,0.1

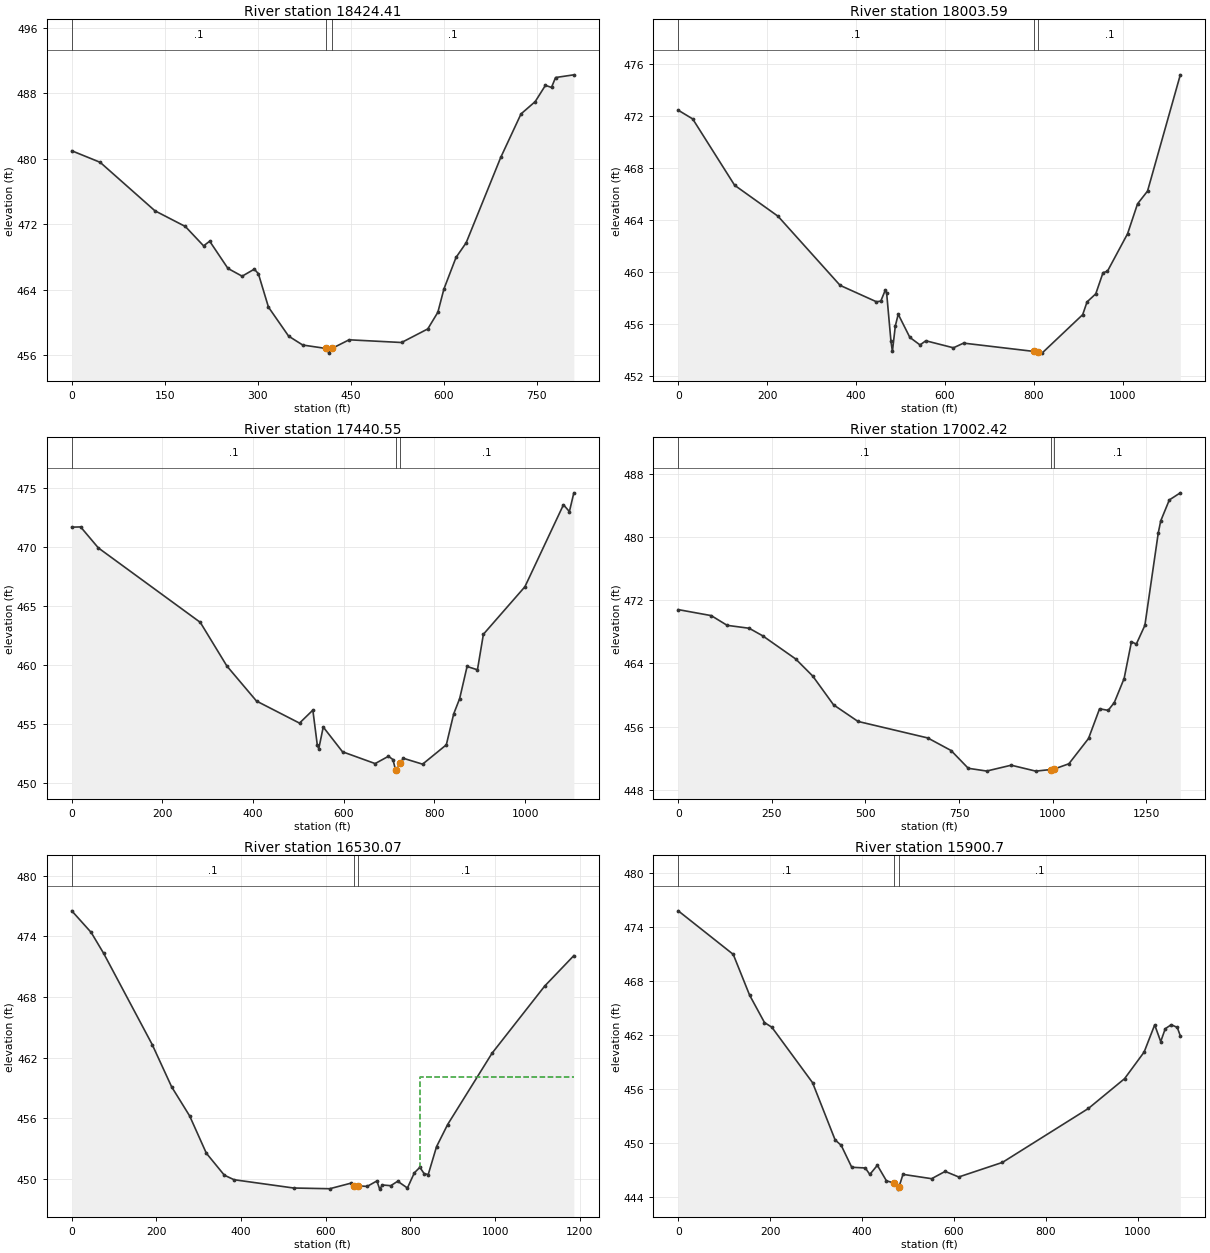
Type RM Length L Ch R = 1 ,18424.41,414.73,420.81,409.4
Node Name=985
XS GIS Cut Line= 4
2442505.14213985 310884.246593522442514.73070335310580.270823523
2442360.82353085310304.9393531832442190.08043402310221.600609109
#Sta/Elev= 30
       0  480.99   45.78  479.58  134.08  473.65  183.13  471.73  212.56  469.36
  222.37  469.93   251.8   466.6   274.7  465.65  294.32  466.51  300.86  465.96
  317.13  461.87  349.65  458.32  372.42  457.23  409.22  456.82  414.69  456.24
  419.42  456.81  447.21  457.87  531.76  457.54  574.03   459.2  590.29  461.24
  600.04  464.08  619.55  467.94  635.93  469.74  691.62  480.17  724.38   485.5
  747.31  487.01  763.69  488.99  773.52  488.74  780.07  489.95  809.55  490.28
#Mann= 3 , 0 , 0
       0      .1       0  409.22    .045       0  419.42      .1       0
Bank Sta=409.22,419.42
XS Rating Curve= 0 ,0
Exp/Cntr=0.3,0.1

Type RM Length L Ch R = 1 ,18003.59,533.49,563.05,588.79
Node Name=986
XS GIS Cut Line= 4
2442756.29157195310822.6394332652442872.32677294310477.356331185
2442475.09167503309991.5374209432442350.11390661309933.214374855
#Sta/Elev= 30
       0  472.44   32.52  471.77  126.84  466.67  224.41  464.29  364.26  458.97
  445.97  457.71  455.78  457.76  465.58  458.58  468.85  458.41  478.66  454.67
  481.92  453.89  488.46  455.85     495  456.75  521.15  454.97  544.03  454.39
   557.1  454.71   619.2  454.17  642.08  454.53  800.47  453.89   810.6  453.83
  818.58  453.76   910.1  456.72   919.9   457.7  939.51  458.32  955.85  459.95
  965.66  460.05 1011.05  462.94  1033.5  465.24 1055.96  466.22 1129.73  475.16
#Mann= 3 , 0 , 0
       0      .1       0  800.47    .045       0   810.6      .1       0
Bank Sta=800.47,810.6
XS Rating Curve= 0 ,0
Exp/Cntr=0.3,0.1

Type RM Length L Ch R = 1 ,17440.55,438.92,438.12,436.98
Node Name=987
XS GIS Cut Line= 3
2442789.61893311310812.2247559432442982.63593553 310506.28967227
2443162.46923727309782.407917932
#Sta/Elev= 30
       0  471.71   19.55  471.73   58.66  469.95  283.52  463.64  342.18  459.94
  407.53  456.97  502.41   455.1  531.85   456.2  541.66  453.24  544.93  452.93
  554.75  454.77  597.28  452.67  669.25  451.67  698.69  452.29  708.51  452.01
  714.48  451.11  715.05  451.03  724.54  451.72  731.41  452.12  773.93  451.62
  826.28  453.26  842.63  455.89  855.72  457.18  872.08   459.9  894.98  459.62
  908.06  462.63  999.66  466.66 1084.72  473.61  1097.8  473.03 1107.62  474.62
#Mann= 3 , 0 , 0
       0      .1       0  714.48    .045       0  724.54      .1       0
Bank Sta=714.48,724.54
XS Rating Curve= 0 ,0
Exp/Cntr=0.3,0.1

Type RM Length L Ch R = 1 ,17002.42,478.89,472.35,458.23
Node Name=988
XS GIS Cut Line= 4
2442840.86161278310808.2828346942443428.57303578310546.073385358
2443542.99242637310010.6663196832443560.31489828309861.560646772
#Sta/Elev= 30
       0  470.81    88.2  470.05  130.67  468.82  189.47  468.45  225.41   467.5
  313.61  464.57  359.34   462.4  414.88  458.76  480.21  456.66   666.5  454.57
  728.79  452.98  774.69  450.73  823.86  450.38  889.43  451.12     955  450.37
  994.56  450.57 1004.53  450.64 1043.52   451.3 1095.97   454.5 1125.48  458.26
 1148.43  458.06 1164.82  459.05 1191.05  462.09 1210.63  466.74 1223.68  466.45
 1246.52  468.82 1282.42  480.56 1288.94  482.05 1311.79  484.69 1341.16  485.59
#Mann= 3 , 0 , 0
       0      .1       0  994.56    .045       0 1004.53      .1       0
Bank Sta=994.56,1004.53
XS Rating Curve= 0 ,0
Exp/Cntr=0.3,0.1

Type RM Length L Ch R = 1 ,16530.07,603.1,629.37,596.14
XS GIS Cut Line= 2
 2444049.9198902310904.1251626912443854.61877161309734.127174601
#Sta/Elev= 30
       0  476.51   45.87  474.37   75.37   472.3  190.05  463.28  235.93   459.1
  278.52  456.22  317.85  452.54  360.44  450.36  383.38  449.91  524.28  449.09
  609.48  449.02  658.63  449.56   666.4  449.28  677.02   449.3  697.95  449.25
  720.89  449.79  727.44  448.98  733.99  449.39  753.65  449.32  770.04  449.76
  792.98  449.09  809.36  450.59  822.47  451.14   832.3  450.52  842.13  450.42
  861.79  453.18     888  455.37  992.86  462.42 1117.38  469.07 1186.19  472.08
#Mann= 3 , 0 , 0
       0      .1       0   666.4    .045       0  677.02      .1       0
#XS Ineff= 2 , 0
                          823.44          460.09
Permanent Ineff=
       F       F
Bank Sta=666.4,677.02
XS Rating Curve= 0 ,0
Exp/Cntr=0.3,0.1

Type RM Length L Ch R = 1 ,15900.7 ,408.16,467.11,485.31
Node Name=990
XS GIS Cut Line= 3
2444525.51408336310674.4655170142444570.13538519310465.619806096
2444316.01384619309624.102788359
#Sta/Elev= 30
       0  475.75  119.72  470.91  155.32  466.38  187.67  463.34  203.85  462.81
  292.28  456.66  341.48  450.29   354.6   449.7  377.56  447.26  407.08  447.18
  416.92  446.46  433.32  447.48     453  445.76  470.36  445.49  479.24  444.83
  480.32  445.06  489.08  446.47   551.4  445.99  580.92   446.8  610.44  446.18
  705.56   447.8  892.53  453.79  971.25   457.1 1013.89  460.06 1036.85  463.08
 1049.97  461.22 1059.81  462.65 1072.93   463.1 1086.05  462.79 1092.61  461.86
#Mann= 3 , 0 , 0
       0      .1       0  470.36    .045       0  480.32      .1       0
Bank Sta=470.36,480.32
XS Rating Curve= 0 ,0
Exp/Cntr=0.3,0.1