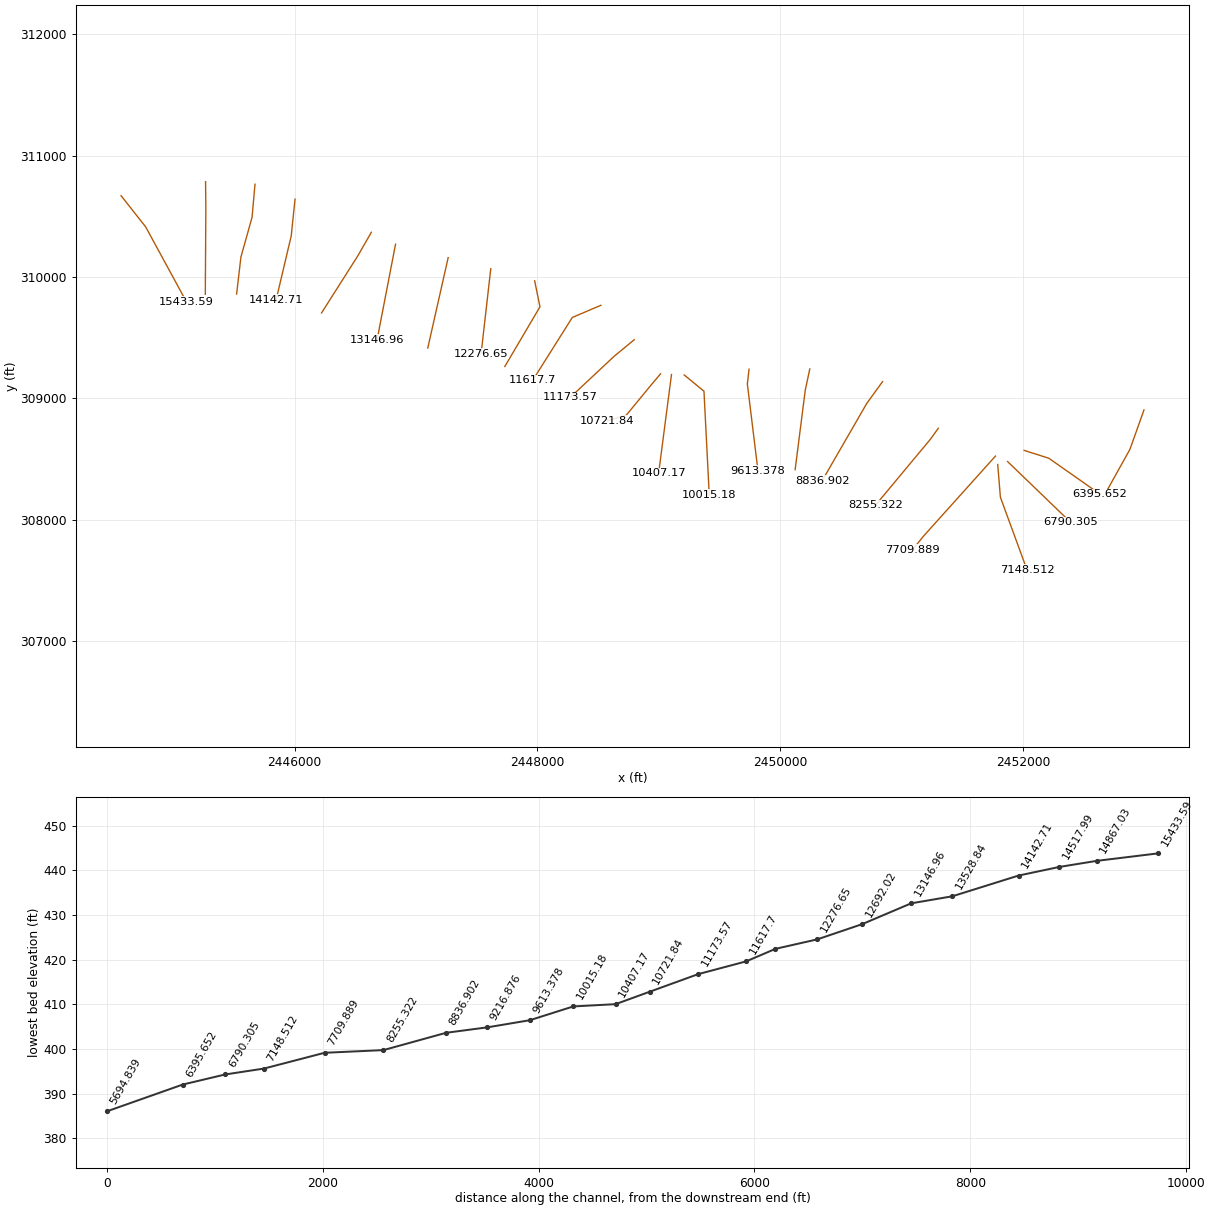
HEC-RAS study ElksRun.prj: ElksRun

--- ElksRun.g04 (geometry) --- (continued)

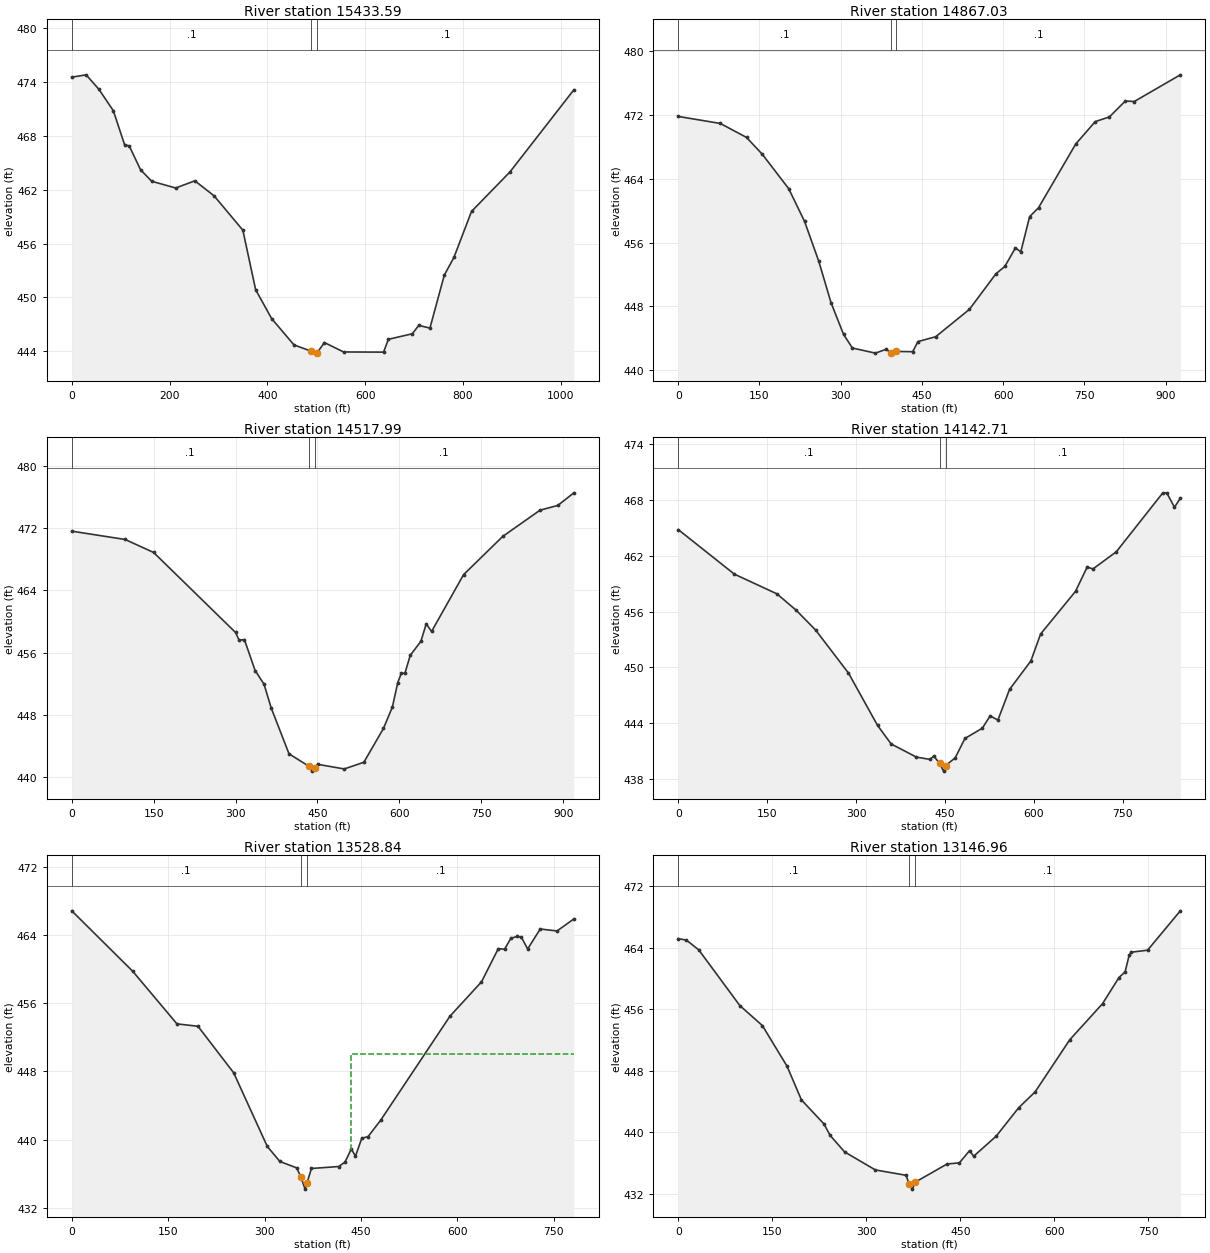
Type RM Length L Ch R = 1 ,15433.59,547.55,566.56,541.75
Node Name=991
XS GIS Cut Line= 3
2444570.72265436  310669.0406591 2444773.2570262310412.255739599
2445107.80032036 309797.41937086
#Sta/Elev= 30
       0  474.55   29.43  474.81    55.6  473.19   85.03  470.81  107.93  467.04
  117.74  466.87  140.63  464.24  163.52  462.95  212.58   462.2  251.82     463
  291.07  461.33  349.94   457.5  376.11  450.87  408.82  447.65  454.61  444.71
   490.3  444.01   500.4   443.8  502.23  443.86  516.75  444.98     556  443.93
  637.77  443.91  647.59  445.34  696.65  445.96  709.73  446.89  732.63  446.59
  762.07   452.5  781.69  454.46  817.67  459.59  896.17  463.98    1027  473.14
#Mann= 3 , 0 , 0
       0      .1       0   490.3    .045       0  502.23      .1       0
Bank Sta=490.3,502.23
XS Rating Curve= 0 ,0
Exp/Cntr=0.3,0.1

Type RM Length L Ch R = 1 ,14867.03,355.17,349.04,339.76
Node Name=992
XS GIS Cut Line= 3
2445266.67795536310784.3130663482445268.96207152310564.257732183
2445264.59495428309857.394644603
#Sta/Elev= 30
       0  471.83   77.67  470.95  126.21  469.19  155.34  467.07  203.89  462.77
  233.16  458.67  259.34  453.68  282.25  448.43  305.15  444.49  321.52  442.77
  364.06  442.13   383.7  442.61  392.77  442.19  402.67  442.34  432.79  442.31
   442.6  443.58  475.33  444.19  537.51  447.62   586.6  452.09  602.96  453.01
  622.59  455.34  632.41  454.84  648.78  459.26  665.14  460.37  733.86  468.37
  769.86  471.18  796.04  471.77  825.49  473.77  841.86   473.7  926.94  477.05
#Mann= 3 , 0 , 0
       0      .1       0  392.77    .045       0  402.67      .1       0
Bank Sta=392.77,402.67
XS Rating Curve= 0 ,0
Exp/Cntr=0.3,0.1

Type RM Length L Ch R = 1 ,14517.99,370.63,375.28,371.5
Node Name=993
XS GIS Cut Line= 4
2445673.86152419310763.2760349362445649.52659911310490.615162939
2445557.87619185310163.5902264422445522.46582961 309859.47764568
#Sta/Elev= 30
       0  471.62   97.77  470.55  149.91  468.88  299.87   458.6   306.4  457.61
   316.2  457.67  335.79   453.7  352.12  451.94  365.18   448.9  397.84  442.99
  433.71  441.41  440.29  440.76  444.57  441.19  450.09  441.64  499.07  441.04
  534.99   441.9  570.92  446.26  587.24  449.01  597.04  452.15  603.57  453.34
   610.1  453.34  619.88  455.64  639.43  457.46   649.2   459.7  658.97  458.72
   717.6  466.03  789.25  470.94  857.65  474.32  890.22  474.93  919.54  476.55
#Mann= 3 , 0 , 0
       0      .1       0  433.71    .045       0  444.57      .1       0
Bank Sta=433.71,444.57
XS Rating Curve= 0 ,0
Exp/Cntr=0.3,0.1

Type RM Length L Ch R = 1 ,14142.71,568.75,613.87,558.69
Node Name=994
XS GIS Cut Line= 3
2446003.63022161310640.5886162672445972.38586153310338.559036598
2445847.40809311309809.486603931
#Sta/Elev= 30
       0  464.81   94.68  460.02  166.51   457.9  199.16  456.13  231.81  454.01
  287.32  449.38  336.39  443.75  359.31  441.76  401.89  440.35  424.81   440.1
  431.36  440.46  440.96  439.68  447.74  438.84  451.28  439.44  467.39  440.27
  483.76  442.35  513.24  443.46  526.33  444.78  539.43  444.33  559.08  447.62
  595.11  450.69  611.48  453.58  670.43  458.17  690.08  460.78   699.9  460.58
   739.2  462.42   817.8  468.76  824.35  468.76  837.45  467.21  847.27  468.18
#Mann= 3 , 0 , 0
       0      .1       0  440.96    .045       0  451.28      .1       0
Bank Sta=440.96,451.28
XS Rating Curve= 0 ,0
Exp/Cntr=0.3,0.1

Type RM Length L Ch R = 1 ,13528.84,358,381.88,405.49
Node Name=995
XS GIS Cut Line= 3
2446632.26840003 310367.720395612446519.78831002310171.921902686
2446221.92473252309703.255517185
#Sta/Elev= 30
       0  466.82    94.9  459.73  163.63  453.57  196.35  453.29  251.94  447.83
   304.2   439.2   323.8  437.44  349.94  436.69  356.11  435.68     363   434.2
  366.12  434.95   372.8  436.62  415.27  436.85  425.07  437.37  434.87   438.9
   441.4  438.07   451.2  440.16     461  440.36   480.6  442.28  588.39  454.47
  637.39  458.49  663.52  462.38  673.32  462.32  683.12   463.6  692.92  463.82
  699.46  463.73  709.26  462.35  728.86  464.69  754.99  464.46  781.12  465.87
#Mann= 3 , 0 , 0
       0      .1       0  356.11    .045       0  366.12      .1       0
#XS Ineff= 2 , 0
                          434.03             450
Permanent Ineff=
       F       F
Bank Sta=356.11,366.12
XS Rating Curve= 0 ,0
Exp/Cntr=0.3,0.1

Type RM Length L Ch R = 1 ,13146.96,449.82,454.94,450.21
Node Name=996
XS GIS Cut Line= 3
2446831.60953678310269.6674420982446755.88954386309877.392964184
2446679.81062777309483.258909941
#Sta/Elev= 30
       0   465.2    13.1  465.01   32.75  463.74   98.24   456.5  134.26  453.89
  173.56  448.61  196.48  444.23   232.5   441.1  242.33  439.61  265.25  437.47
  314.37  435.12  363.49  434.42  368.34  433.28  373.32  432.62  378.37  433.54
  428.89  435.89  448.47  436.04  464.79  437.63  471.31   436.9  507.21  439.51
  543.11  443.21  569.22  445.26   624.7  452.06  676.91  456.75  703.02  460.14
  712.81  460.87  719.34  463.04   722.6  463.44  748.71   463.7  800.93  468.82
#Mann= 3 , 0 , 0
       0      .1       0  368.34    .045       0  378.37      .1       0
Bank Sta=368.34,378.37
XS Rating Curve= 0 ,0
Exp/Cntr=0.3,0.1

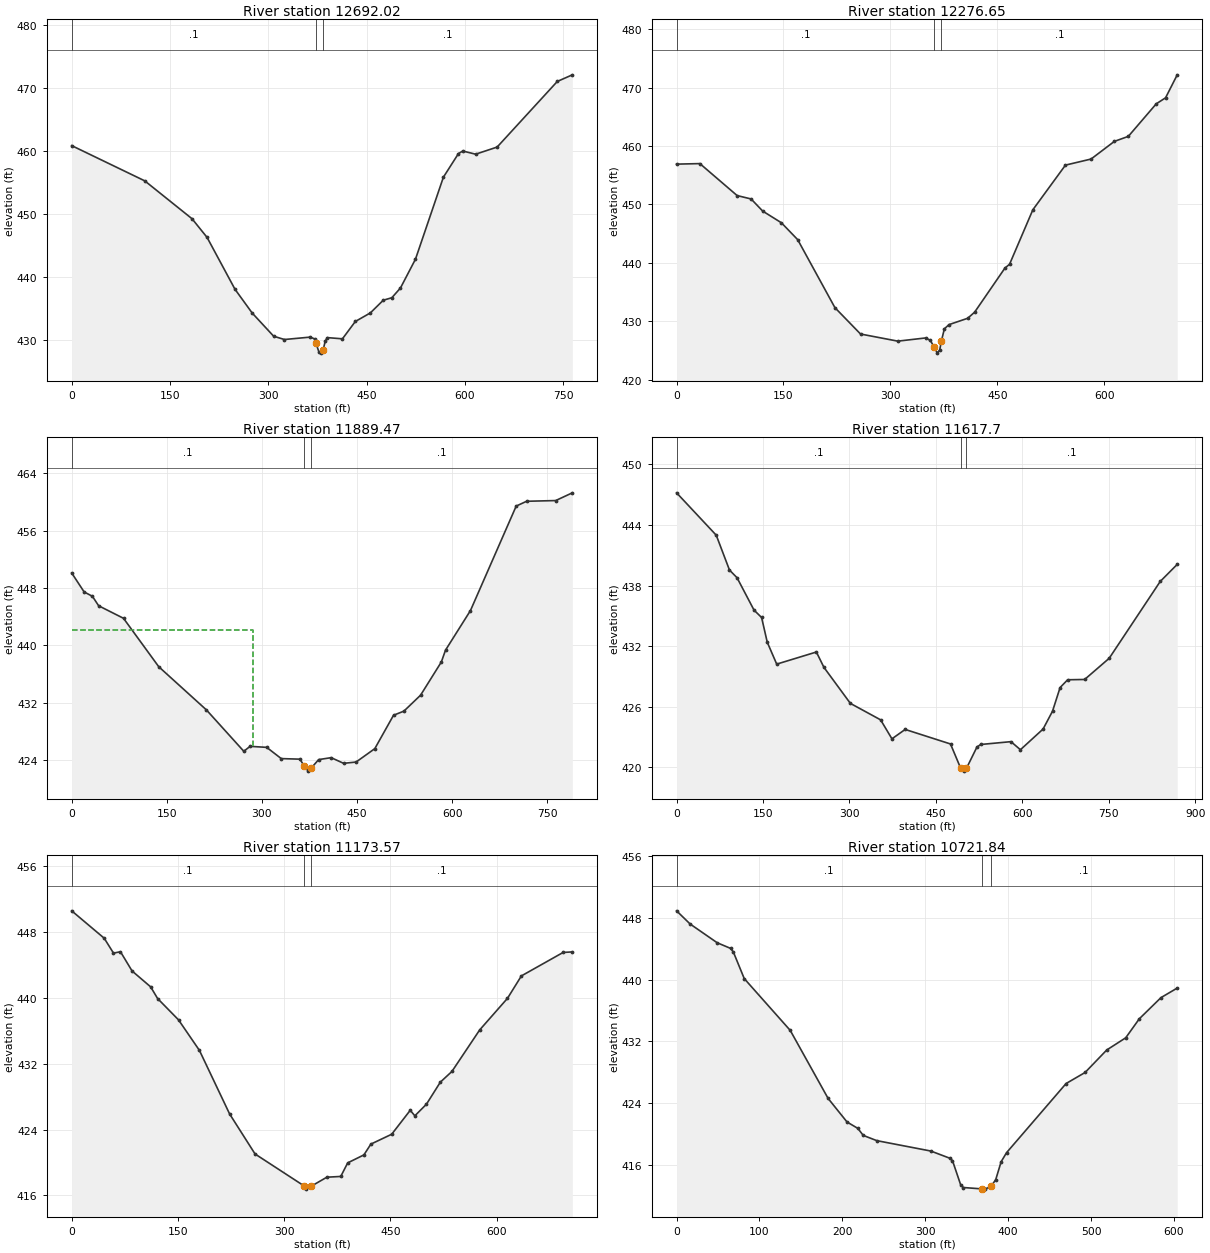
Type RM Length L Ch R = 1 ,12692.02,410.68,415.37,414.3
Node Name=997
XS GIS Cut Line= 2
2447265.15328911 310159.087938862447096.97744437309414.050715014
#Sta/Elev= 30
       0  460.87  111.45  455.28  183.57  449.27  206.52  446.31  249.13  438.08
  275.36  434.31  308.14  430.63  324.53  430.11  363.86  430.49  370.42  430.22
  372.62  429.51  376.97   428.2  380.25  427.95  383.65  428.46  386.81  429.87
  390.09  430.41  413.03  430.22   432.7  432.97  455.65  434.33  475.31  436.34
  488.43  436.74  501.54  438.28  524.49  442.86   567.1  455.87  590.05  459.61
   596.6  460.01  616.27  459.51  649.05  460.64  740.84  471.05  763.78   472.1
#Mann= 3 , 0 , 0
       0      .1       0  372.62    .045       0  383.65      .1       0
Bank Sta=372.62,383.65
XS Rating Curve= 0 ,0
Exp/Cntr=0.3,0.1

Type RM Length L Ch R = 1 ,12276.65,398.33,387.18,372.24
Node Name=998
XS GIS Cut Line= 2
2447615.97181319310066.8624015152447536.40471511309368.842144027
#Sta/Elev= 30
       0  456.89   32.68  456.98   84.96  451.51  104.56  450.93   120.9  448.85
  147.04  446.86  169.92  443.97   222.2  432.33  258.14  427.82  310.42   426.6
  349.64  427.15  356.17  426.72  361.57  425.54  365.97  424.55  369.24   425.1
  371.75  426.69  375.78  428.71  382.31  429.43  408.45  430.51  418.26  431.56
  460.74   439.1  467.27  439.76  499.95  449.08  545.69  456.72  581.64  457.76
  614.31  460.78  633.92  461.64  673.13  467.21   686.2  468.24  702.54  472.17
#Mann= 3 , 0 , 0
       0      .1       0  361.57    .045       0  371.75      .1       0
Bank Sta=361.57,371.75
XS Rating Curve= 0 ,0
Exp/Cntr=0.3,0.1

Type RM Length L Ch R = 1 ,11889.47,271.56,271.77,269.25
XS GIS Cut Line= 3
2447977.44549969309968.2083993552448021.18753819309753.663224772
2447731.65596503309262.083827347
#Sta/Elev= 30
       0   450.1   19.61  447.45   32.68  446.84   42.48  445.52    81.7  443.77
  137.26  437.01  212.42  430.98  271.42   425.2  281.26  425.89  307.49  425.75
  330.44  424.18  359.95   424.1  367.07  423.08  373.06  422.43  377.06   422.8
  389.46  424.04  409.13  424.31   428.8  423.52  448.47   423.7  477.98  425.57
  507.49  430.23  523.89  430.81  550.12  433.03   582.9  437.67  589.46  439.32
  628.81  444.85  700.94  459.44  717.33  460.11  763.24  460.21  789.47  461.29
#Mann= 3 , 0 , 0
       0      .1       0  367.07    .045       0  377.06      .1       0
#XS Ineff= 2 , 0
          286.65  442.19
Permanent Ineff=
       F       F
Bank Sta=367.07,377.06
XS Rating Curve= 0 ,0
Exp/Cntr=0.3,0.1

Type RM Length L Ch R = 1 ,11617.7 ,451.61,444.13,435.83
XS GIS Cut Line= 3
2448523.18161294309766.160903186 2448287.8067556309666.178819686
2447960.78181911309147.521064356
#Sta/Elev= 30
       0  447.19   68.85  442.99    91.8  439.54  104.91  438.78  134.42  435.57
  147.54  434.84  157.37  432.39  173.77  430.22  242.62  431.42  255.73   429.9
  301.63  426.33   354.1   424.7  373.77  422.82  396.72  423.75  475.41  422.31
  493.01  419.91  498.37  419.62  503.02  419.89  521.32  422.01  527.88  422.26
  580.34  422.54  596.73  421.74  636.08  423.79  652.47  425.56  665.59   427.9
   678.7  428.67  708.21   428.7  750.84   430.8  839.37  438.41  868.88   440.1
#Mann= 3 , 0 , 0
       0      .1       0  493.01    .045       0  503.02      .1       0
Bank Sta=493.01,503.02
XS Rating Curve= 0 ,0
Exp/Cntr=0.3,0.1

Type RM Length L Ch R = 1 ,11173.57,436.36,451.73,447.88
Node Name=1000
XS GIS Cut Line= 3
2448798.13283469309482.8780051922448633.57870185309347.485559434
2448273.22607611309010.045617521
#Sta/Elev= 30
       0  450.59    45.9  447.26   59.01  445.45   68.85  445.62   85.24  443.28
  111.46  441.35   121.3  439.93  150.81  437.34  180.31  433.63   222.9  425.91
  258.87  421.04  327.73  417.18  330.79  416.77  337.64   417.1  360.22  418.22
  379.83  418.31  389.64  419.96  412.53  420.93  422.34  422.24  451.76  423.44
  477.92  426.35  484.45  425.68   500.8  427.09  520.42  429.77  536.77  431.07
     576  436.12  615.23  439.96  634.85  442.68   693.7  445.53  706.77   445.6
#Mann= 3 , 0 , 0
       0      .1       0  327.73    .045       0  337.64      .1       0
Bank Sta=327.73,337.64
XS Rating Curve= 0 ,0
Exp/Cntr=0.3,0.1

Type RM Length L Ch R = 1 ,10721.84,298.48,314.68,335.58
Node Name=1001
XS GIS Cut Line= 4
2449014.76068227309201.6781082752448942.79593119309117.142516181
2448731.47778428308860.0721641932448577.33865686 308816.33012569
#Sta/Elev= 30
       0  448.91   16.33   447.2   48.98  444.77   65.31  444.03   68.57  443.55
   81.63  440.12  137.12   433.4  182.79  424.58  205.63  421.52  218.68  420.69
  225.21  419.78  241.52   419.1  306.77  417.75  329.61  416.82  332.87  416.51
  342.66   413.4  345.92  413.02  368.25  412.84  372.02  412.81  379.49  413.18
  385.07  414.05   391.6  416.37  398.12  417.54  469.95  426.51  492.84  427.94
     519  430.86  541.89  432.44  558.24   434.9   584.4  437.65  604.02  438.89
#Mann= 3 , 0 , 0
       0      .1       0  368.25    .045       0  379.49      .1       0
Bank Sta=368.25,379.49
XS Rating Curve= 0 ,0
Exp/Cntr=0.3,0.1

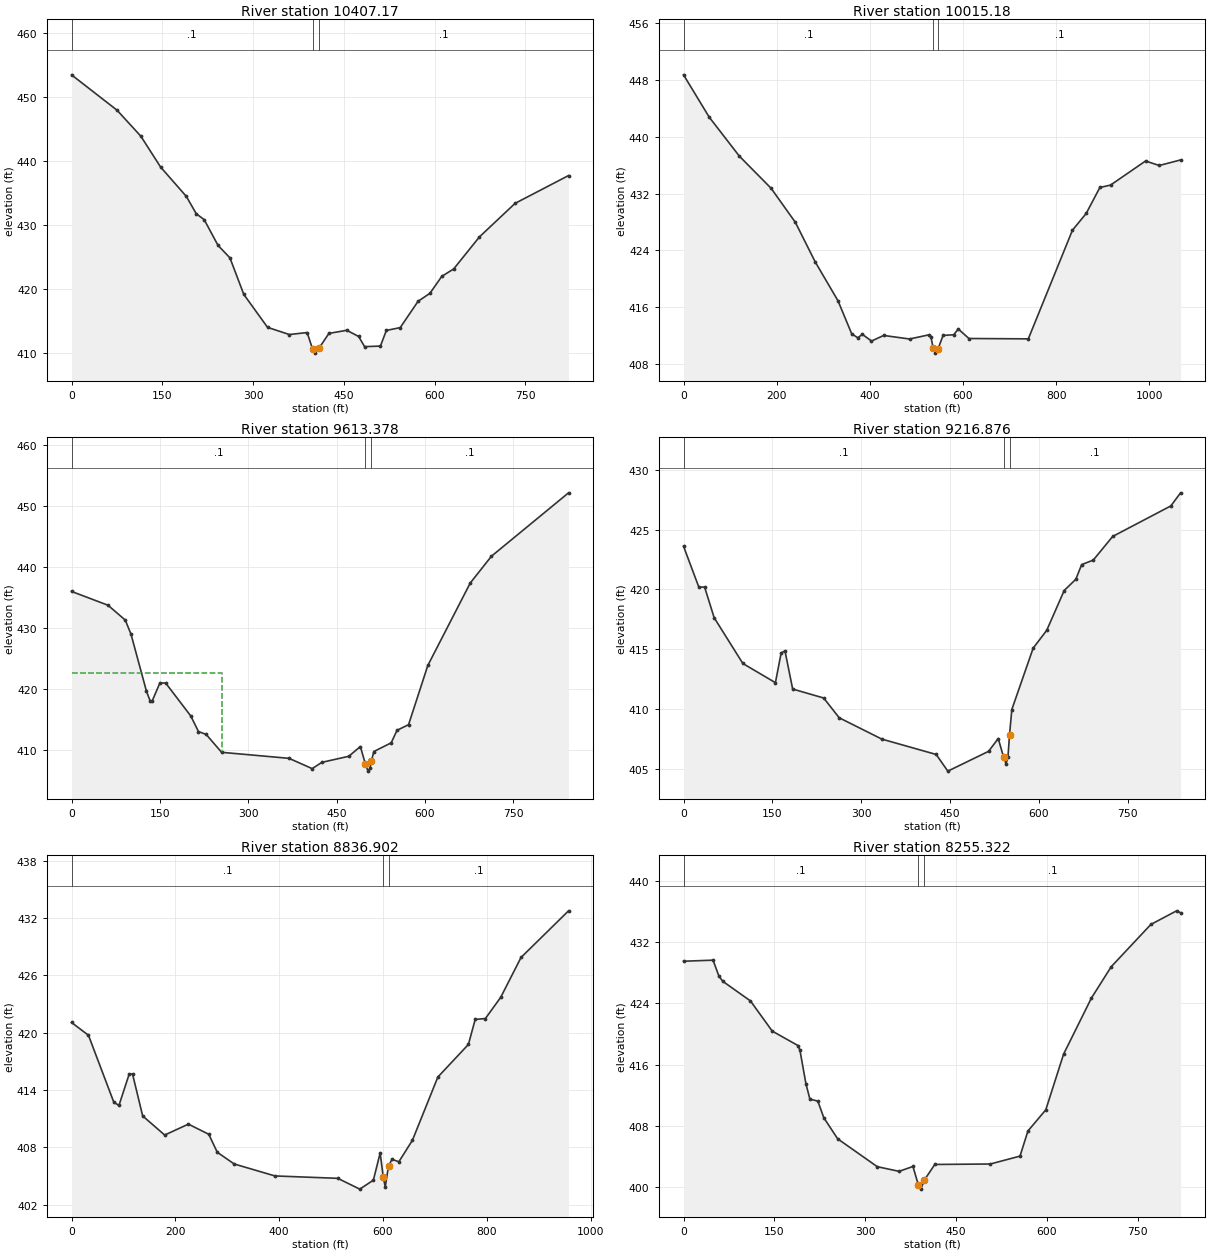
Type RM Length L Ch R = 1 ,10407.17,382.95,391.99,385.39
XS GIS Cut Line= 2
2449104.74475427309196.2624366882448998.51366752308381.824104935
#Sta/Elev= 30
       0  453.45   75.26  447.93  114.53  443.88  147.25  439.06  189.79  434.48
  206.15  431.78  219.24  430.86  242.15  426.84  261.78   424.9  284.69   419.2
  323.95  414.06  359.95  412.94   389.4  413.25  398.55  410.61  402.49  410.04
  408.69  410.77  425.39  413.12  454.84   413.6  474.48  412.64  484.29  411.05
  510.47  411.14  520.29  413.58  543.19  414.02  572.64  418.12  592.28  419.37
  611.91  422.02  631.55  423.17  674.08  428.17  732.99   433.4  821.34  437.74
#Mann= 3 , 0 , 0
       0      .1       0  398.55    .045       0  408.69      .1       0
Bank Sta=398.55,408.69
XS Rating Curve= 0 ,0
Exp/Cntr=0.3,0.1

Type RM Length L Ch R = 1 ,10015.18,393.41,401.8,401.48
XS GIS Cut Line= 3
2449209.48371802309192.3477463572449372.23437677309058.530428693
2449415.63488053308203.184042275
#Sta/Elev= 30
       0  448.73   55.11  442.77  119.94  437.27  188.01  432.75  240.12  427.95
  282.62  422.39  331.65   416.9  361.07  412.25  374.14  411.69  383.95  412.18
  403.56  411.23  429.72  412.02  485.29  411.52  527.78  412.12  531.05  411.83
   536.2  410.22  540.86  409.53  546.22  410.08   557.2  412.02  580.08  412.12
  589.89  412.93  612.77  411.59  740.26  411.54  835.06  426.85  864.48   429.2
   893.9  432.86  916.78   433.2  991.96  436.59 1021.38  435.96 1067.15  436.74
#Mann= 3 , 0 , 0
       0      .1       0   536.2    .045       0  546.22      .1       0
Bank Sta=536.2,546.22
XS Rating Curve= 0 ,0
Exp/Cntr=0.3,0.1

Type RM Length L Ch R = 1 ,9613.378,401.81,396.5,387.43
Node Name=1004
XS GIS Cut Line= 3
2449743.44459236309240.2134642752449729.63359636309117.109707847
2449817.11800145308402.653459609
#Sta/Elev= 30
       0  435.96   61.94  433.69   91.28  431.25  101.06  428.91  127.15  419.59
  133.69  417.91  136.96  417.98  150.05  420.93  159.87  420.91   202.4  415.51
  215.49  412.95  228.57  412.48  254.75  409.54  369.26  408.55  408.52  406.86
  424.88  407.89  470.69  408.89  490.32  410.49  498.82  407.62   503.4  406.45
  506.67  406.93  508.84  408.04  513.22  409.67  542.66   411.1  552.48  413.15
  572.11  414.08  604.83  423.81  676.81  437.34   712.8  441.74  843.67  452.15
#Mann= 3 , 0 , 0
       0      .1       0  498.82    .045       0  508.84      .1       0
#XS Ineff= 2 , 0
          255.77   422.5
Permanent Ineff=
       F       F
Bank Sta=498.82,508.84
XS Rating Curve= 0 ,0
Exp/Cntr=0.3,0.1

Type RM Length L Ch R = 1 ,9216.876,390.58,379.97,366.24
XS GIS Cut Line= 3
2450243.70868368309242.0874762682450206.21532036 309065.03566502
2450123.18070953308412.114070609
#Sta/Elev= 30
       0   423.6   25.85  420.19   35.55   420.2   51.71  417.64  100.18  413.82
  155.12  412.22  164.82   414.7  171.28  414.87  184.25  411.69  236.65  410.94
  262.84  409.29  334.88  407.51  426.57  406.23  446.21  404.84  514.98  406.49
  531.35  407.56  540.23  406.03  544.45  405.46  547.73  406.03  550.38  407.85
  554.27  409.98  590.29   415.1  613.22  416.59  642.69  419.91  662.33  420.85
  672.16  422.07  691.81  422.45  724.55  424.42  822.79  426.97  839.16  428.06
#Mann= 3 , 0 , 0
       0      .1       0  540.23    .045       0  550.38      .1       0
Bank Sta=540.23,550.38
XS Rating Curve= 0 ,0
Exp/Cntr=0.3,0.1

Type RM Length L Ch R = 1 ,8836.902,579.56,581.58,570.09
Node Name=1005
XS GIS Cut Line= 3
2450843.60184085  309137.9393906 2450713.4301852308958.302938849
2450345.77376828 308321.41805777
#Sta/Elev= 30
       0  421.07   32.62  419.73   81.56  412.71   91.35  412.39  110.92  415.64
  117.45  415.69  137.02  411.29  179.43  409.29  225.11  410.43  264.33  409.37
  280.67  407.49  313.36  406.26   391.8  405.01  512.73  404.76  555.22  403.63
  581.36  404.57  594.44  407.42  600.46  404.86  604.24  403.85   610.6   406.1
  617.32  406.75  630.39  406.49  656.54  408.74  705.56  415.36  764.39  418.77
  777.47  421.39  797.08  421.48  826.49  423.69  865.71  427.87  957.23  432.75
#Mann= 3 , 0 , 0
       0      .1       0  600.46    .045       0   610.6      .1       0
Bank Sta=600.46,610.6
XS Rating Curve= 0 ,0
Exp/Cntr=0.3,0.1

Type RM Length L Ch R = 1 ,8255.322,536.47,545.43,540.07
Node Name=1006
XS GIS Cut Line= 3
2451302.68688069 308753.424411612451238.11515944308663.857005432
2450784.02912536308118.120892182
#Sta/Elev= 30
       0   429.5   48.71  429.64   58.46  427.54   64.95  426.87  110.42  424.32
   146.4  420.38  188.94  418.49  192.21  417.85  202.02   413.5  208.57   411.5
  221.65  411.24  231.47  409.08  254.37  406.32   319.8  402.68  355.79  402.07
  378.69  402.71  387.48  400.32  391.78  399.75   397.1  400.89  414.68  402.97
  506.28  403.03  555.36  404.06  568.45  407.34  597.89   410.1  627.33  417.38
  673.14  424.68  705.85  428.78  771.29   434.3  813.82  436.08  820.36  435.83
#Mann= 3 , 0 , 0
       0      .1       0  387.48    .045       0   397.1      .1       0
Bank Sta=387.48,397.1
XS Rating Curve= 0 ,0
Exp/Cntr=0.3,0.1

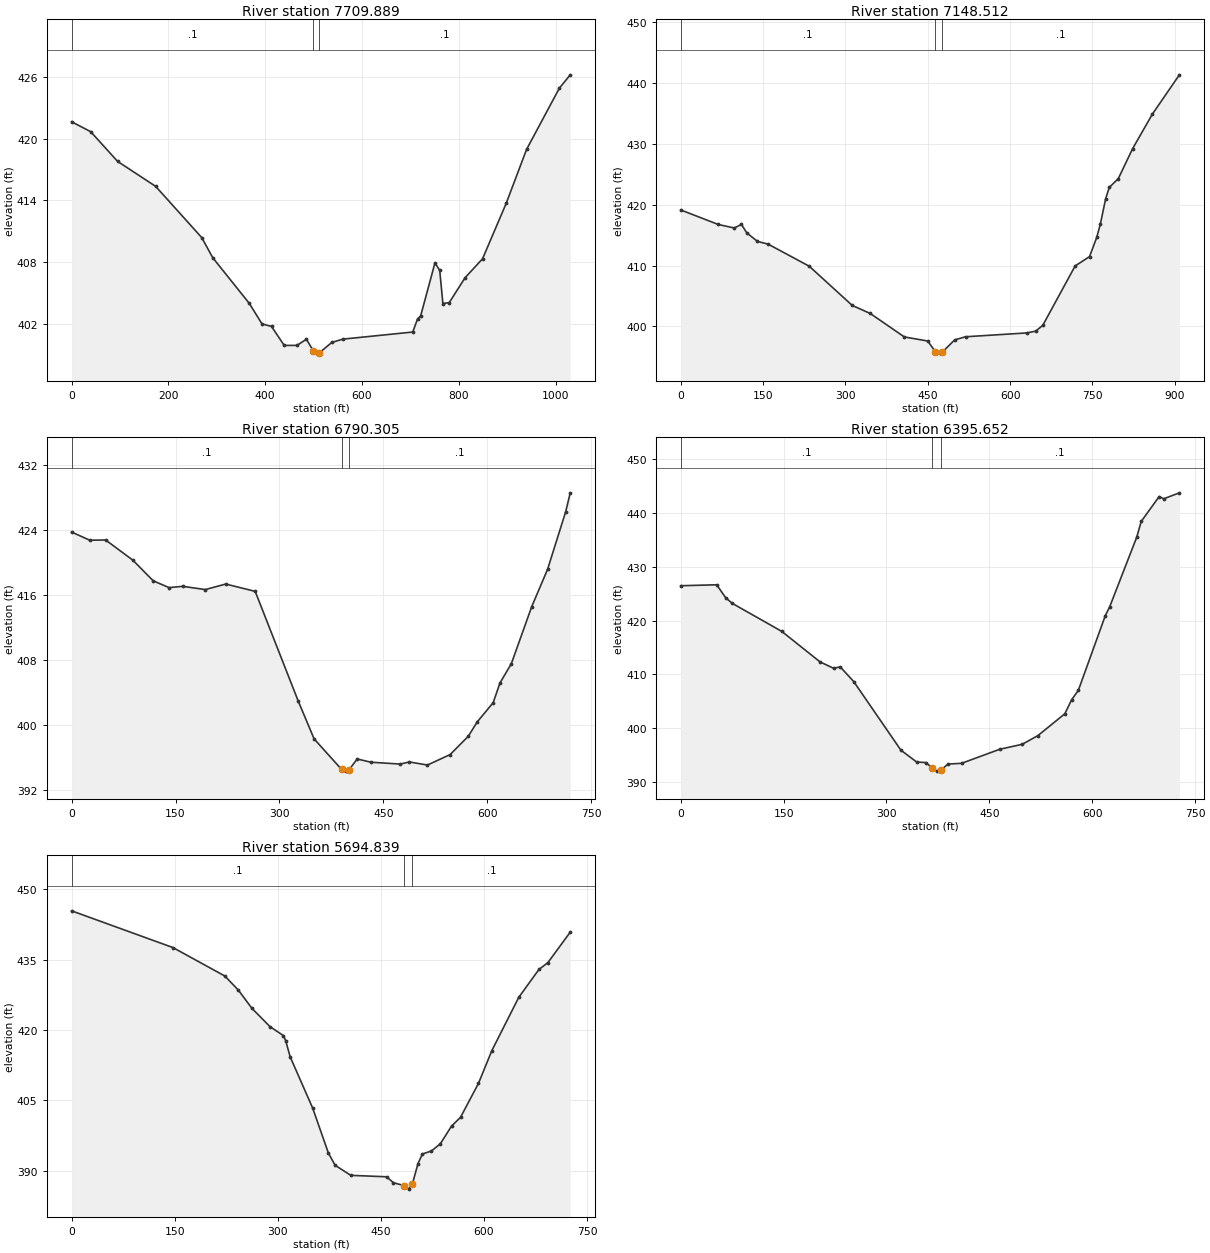
Type RM Length L Ch R = 1 ,7709.889,524.52,561.38,590.45
Node Name=1007
XS GIS Cut Line= 3
2451773.43659537 308524.298557522451181.87511444307866.082354277
2451090.22470719307753.602592349
#Sta/Elev= 30
       0  421.63   39.33  420.67   95.05  417.78  173.72  415.35  268.77  410.38
  291.72  408.41   367.1  403.98  393.33  401.99  412.99  401.74  439.21   399.9
  465.43   399.9   485.1   400.5   499.1  399.38  508.04  399.15  511.47  399.17
  537.54  400.19  560.49  400.51  704.71   401.2  714.54  402.46   721.1  402.78
   750.6  407.92  760.43  407.19  766.99  403.97   780.1  404.06  812.87  406.48
  848.93  408.32  897.88  413.72   939.8  418.94 1007.51  424.89 1030.08  426.19
#Mann= 3 , 0 , 0
       0      .1       0   499.1    .045       0  511.47      .1       0
Bank Sta=499.1,511.47
XS Rating Curve= 0 ,0
Exp/Cntr=0.3,0.1

Type RM Length L Ch R = 1 ,7148.512,340.24,358.21,369.5
Node Name=1008
XS GIS Cut Line= 3
2451791.94147961308454.3429887742451813.93520203308185.306453347
2452033.58830602307585.770907015
#Sta/Elev= 30
       0  419.17    68.3  416.78   97.57   416.2  110.58  416.79  120.33   415.4
  139.85  413.99  159.36  413.54  234.16  409.91   312.5  403.46  345.25  402.14
  407.46  398.28  450.03  397.61  463.93  395.85  472.95  395.62  476.22  395.76
  499.14   397.8  518.79  398.31  630.12  398.94  646.49  399.23  659.59  400.19
  718.53  409.96  744.72  411.49  757.82  414.64  764.37  416.81  774.19  421.04
  780.74  422.88  797.11  424.31  823.31  429.26  859.33  434.94  908.44  441.39
#Mann= 3 , 0 , 0
       0      .1       0  463.93    .045       0  476.22      .1       0
Bank Sta=463.93,476.22
XS Rating Curve= 0 ,0
Exp/Cntr=0.3,0.1

Type RM Length L Ch R = 1 ,6790.305,297.72,394.65,357.8
Node Name=1009
XS GIS Cut Line= 2
2451873.23757686308479.0378212632452391.44388953307979.673006356
#Sta/Elev= 30
       0  423.76   26.17  422.75   49.07  422.78   88.32   420.3  117.76  417.75
  140.66  416.91  160.29  417.07     193  416.67  222.44  417.35  264.96  416.45
  327.12  402.92  350.01  398.27  389.55  394.52  395.81   394.3  399.86   394.4
  412.17   395.8  431.79   395.4  474.32  395.17   487.4  395.43  513.57  395.05
  546.28  396.34  572.45  398.59  585.54  400.38  608.44  402.74  618.25  405.17
   634.6  407.53  664.05  414.57  686.94  419.17  713.11  426.28  719.66  428.59
#Mann= 3 , 0 , 0
       0      .1       0  389.55    .045       0  399.86      .1       0
Bank Sta=389.55,399.86
XS Rating Curve= 0 ,0
Exp/Cntr=0.3,0.1

Type RM Length L Ch R = 1 ,6395.652,737.2,700.81,640.84
Node Name=1010
XS GIS Cut Line= 3
2452009.88330095308571.0012200182452212.84516536 308506.36650677
2452633.71243386308211.098068431
#Sta/Elev= 30
       0  426.48   52.43  426.66   65.54  424.25   75.37  423.19  147.47  417.99
  203.17  412.33  222.83  411.15  232.65   411.4   252.3  408.67  321.07  395.93
  343.99  393.74  357.09  393.63  366.93  392.66  373.46  392.04  378.91  392.22
  389.83  393.35  409.48  393.49  465.15   396.1   497.9  397.02  520.82  398.64
  560.11   402.7  569.94  405.29  579.76  407.04  619.06  420.91  625.61  422.61
   664.9  435.49  671.45  438.42  697.65  443.05   704.2  442.63  727.12  443.74
#Mann= 3 , 0 , 0
       0      .1       0  366.93    .045       0  378.91      .1       0
Bank Sta=366.93,378.91
XS Rating Curve= 0 ,0
Exp/Cntr=0.3,0.1

Type RM Length L Ch R = 1 ,5694.839,320.73,349.2,340.65
Node Name=1011
XS GIS Cut Line= 3
2452996.55225936308903.8145307752452880.84350127308579.564195022
2452695.35568328308246.431331098
#Sta/Elev= 30
       0   445.4  147.55  437.56  222.96   431.5  242.63   428.5  262.31  424.62
  288.54  420.73  308.21  418.79  311.49  417.71  318.05  414.26   350.8  403.33
  373.61  393.77  383.38  391.15   406.2     389  458.34  388.69  468.12  387.44
  483.13  386.82  490.93  386.06  495.93   387.2  503.96  391.48  510.48  393.56
  523.52  394.19  536.55  395.73  552.85  399.51  565.88  401.37  591.95  408.59
  611.51  415.61  650.61  426.95  679.94  432.89  692.98  434.35  725.57  440.86
#Mann= 3 , 0 , 0
       0      .1       0  483.13    .045       0  495.93      .1       0
Bank Sta=483.13,495.93
XS Rating Curve= 0 ,0
Exp/Cntr=0.3,0.1