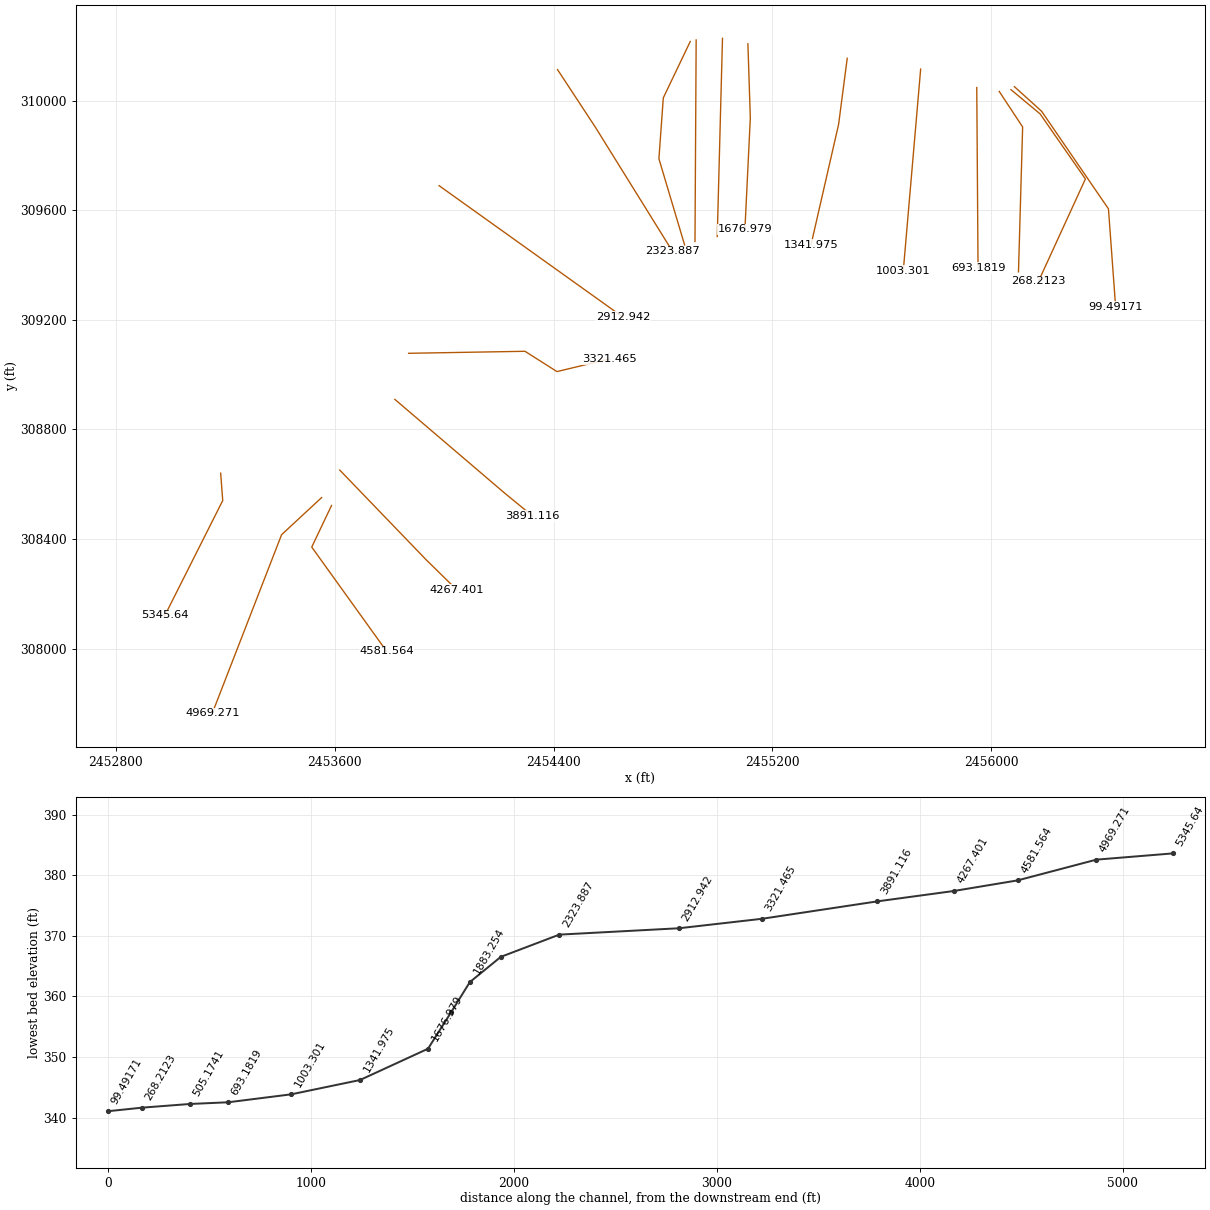
HEC-RAS study ElksRun.prj: ElksRun

--- ElksRun.g04 (geometry) --- (continued)

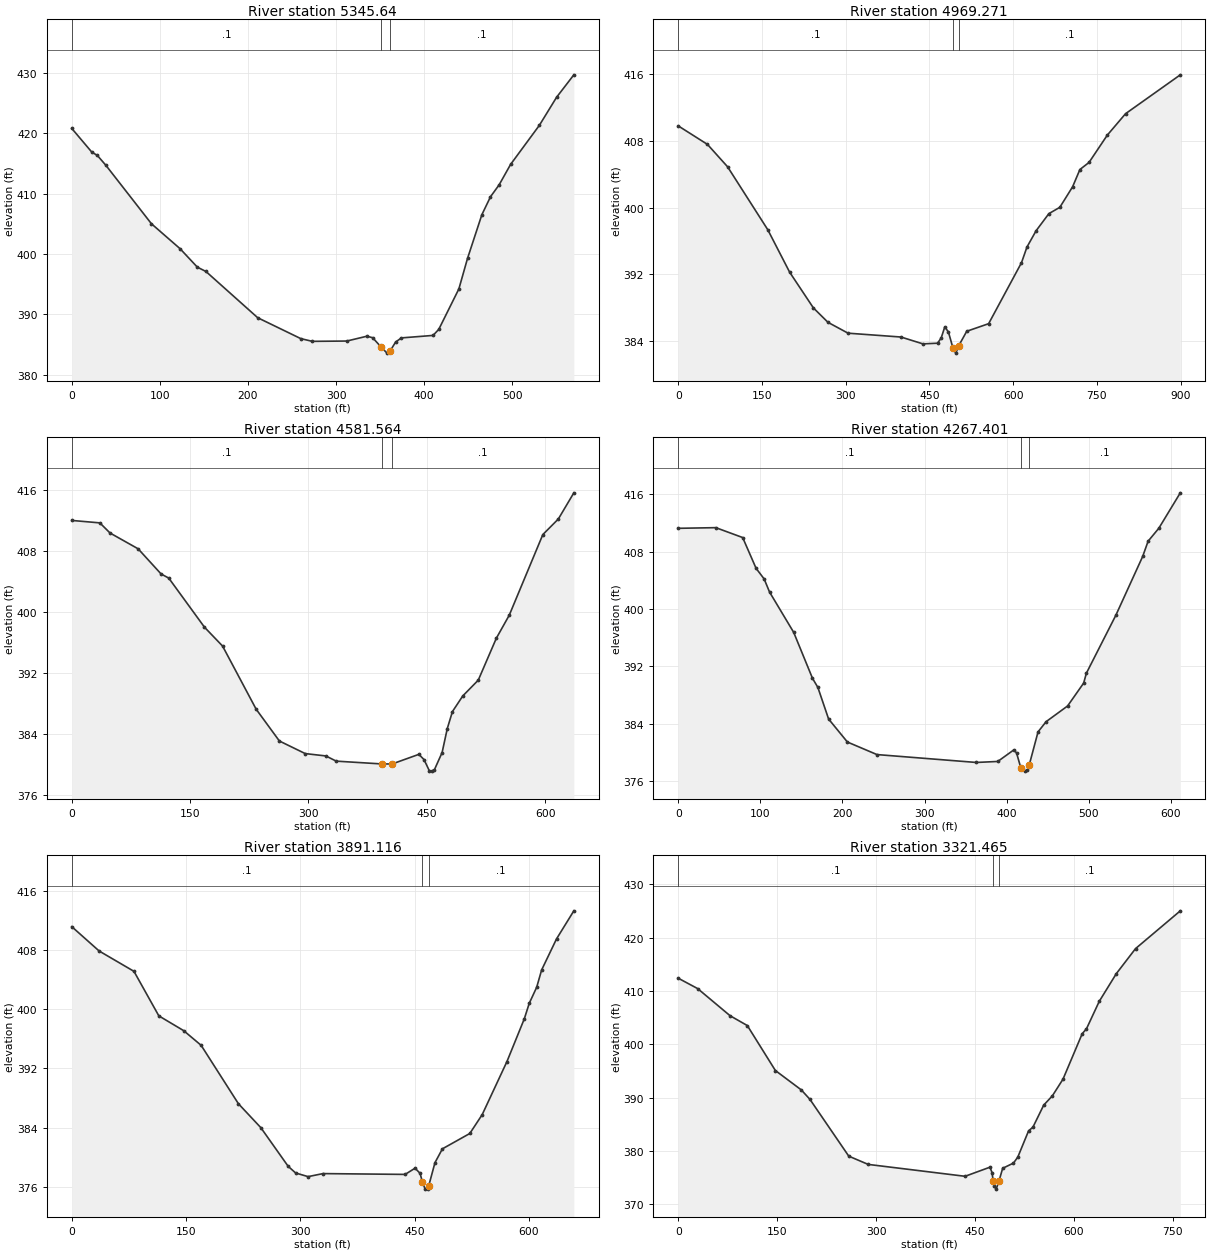
Type RM Length L Ch R = 1 ,5345.64 ,357.43,376.37,321.36
Node Name=1012
XS GIS Cut Line= 3
2453182.76907852308640.1113180222453190.36978512308540.259155527
 2452978.7934366308120.723905355
#Sta/Elev= 30
       0  420.78   22.61  416.88   29.07   416.3   38.76  414.67   90.45     405
  122.98  400.87  142.56  397.82  152.35   397.1  211.08  389.45  260.03  385.99
  273.08  385.54  312.23  385.59  335.07  386.39   341.6  386.14  351.39  384.57
  357.91  383.59  361.37  383.94   367.7  385.43  374.23  386.11  410.12  386.52
  416.65  387.52  439.49  394.22  449.28  399.26  465.59   406.5  475.38  409.47
  485.17  411.44  498.22  414.83  530.85  421.29  550.43  425.94  570.01  429.65
#Mann= 3 , 0 , 0
       0      .1       0  351.39    .045       0  361.37      .1       0
Bank Sta=351.39,361.37
XS Rating Curve= 0 ,0
Exp/Cntr=0.3,0.1

Type RM Length L Ch R = 1 ,4969.271,352.18,387.71,418.31
XS GIS Cut Line= 3
2453552.03835312308551.1095275132453405.56259619308415.483814523
2453151.94105619307763.183938026
#Sta/Elev= 30
       0   409.8   52.36  407.58   88.36   404.9  160.35  397.36  199.62  392.26
  242.14  387.98   268.3  386.25  304.28  384.95  399.12  384.49  438.36  383.67
  464.53  383.75  471.07  384.37  477.61  385.72  484.15  385.07  492.38  383.13
  497.23  382.56  502.54  383.45  516.86  385.18   556.1  386.09  614.97   393.4
  624.78  395.28  641.13  397.23  664.02  399.28  683.65  400.04  706.54   402.5
  719.62  404.57  735.97  405.42  768.68  408.69  801.38  411.26  899.49  415.92
#Mann= 3 , 0 , 0
       0      .1       0  492.38    .045       0  502.54      .1       0
Bank Sta=492.38,502.54
XS Rating Curve= 0 ,0
Exp/Cntr=0.3,0.1

Type RM Length L Ch R = 1 ,4581.564,313.39,314.16,315.3
Node Name=1013
XS GIS Cut Line= 3
2453588.20494744308522.175858349 2453515.8714307308370.274915442
 2453789.3275767307990.227119103
#Sta/Elev= 30
       0  412.01   35.59  411.69   48.53  410.36   84.12  408.29  113.24  404.99
  122.95  404.45  168.24  398.01  191.16  395.54  233.73  387.26  263.19  383.09
  295.94  381.44  322.13  381.13  335.23  380.45  393.36  380.08  406.11  380.08
     440  381.34  446.55  380.65   453.1  379.22  456.37  379.14  459.64  379.31
  469.47  381.58  476.01  384.72  482.56  386.95  495.66     389   515.3  391.07
  538.22  396.57  554.59  399.59  597.16  410.16   616.8   412.2  636.45  415.63
#Mann= 3 , 0 , 0
       0      .1       0  393.36    .045       0  406.11      .1       0
Bank Sta=393.36,406.11
XS Rating Curve= 0 ,0
Exp/Cntr=0.3,0.1

Type RM Length L Ch R = 1 ,4267.401,371.58,376.28,377.09
Node Name=1014
XS GIS Cut Line= 3
2453618.13795844308651.5384605232453933.82236645308324.416411355
2454045.91302152308214.613153264
#Sta/Elev= 30
       0  411.27   45.79  411.36   78.49  409.98   94.85  405.68  104.66   404.2
   111.2  402.38  140.63  396.75  163.53  390.34  170.07  389.07  183.15  384.66
  206.04  381.45  242.02   379.7  363.03   378.6  389.19  378.74  408.82  380.36
  412.09  379.92  417.44  377.77   421.9  377.39  425.17  377.51  427.58  378.28
  438.25  382.87  448.06  384.29  474.22  386.48  493.83  389.68   497.1  391.05
  533.06  399.15  565.75  407.36  572.29  409.47  585.36  411.28  611.52  416.22
#Mann= 3 , 0 , 0
       0      .1       0  417.44    .045       0  427.58      .1       0
Bank Sta=417.44,427.58
XS Rating Curve= 0 ,0
Exp/Cntr=0.3,0.1

Type RM Length L Ch R = 1 ,3891.116,544.83,569.65,546.12
Node Name=1015
XS GIS Cut Line= 3
2453819.88985153308909.4313174342454222.50190718 308566.29617694
2454323.15492111308483.943651348
#Sta/Elev= 30
       0  411.16   35.92  407.87   81.64  405.12  114.29   399.1  146.94   397.1
   169.8  395.12  218.78  387.22  248.17  383.99  284.09  378.76  293.89  377.86
  310.21  377.37  329.81  377.78  437.57  377.67  450.63  378.51  457.16  377.82
  460.28  376.66  463.69  375.72  466.95  375.68  468.41  376.07  476.75  379.26
  486.55  381.13  522.47   383.2  538.75  385.75  571.26  392.93  594.02   398.7
  600.52   400.8  610.28  402.97  616.78  405.31  636.29   409.5  659.05   413.3
#Mann= 3 , 0 , 0
       0      .1       0  460.28    .045       0  468.41      .1       0
Bank Sta=460.28,468.41
XS Rating Curve= 0 ,0
Exp/Cntr=0.3,0.1

Type RM Length L Ch R = 1 ,3321.465,440.29,408.52,398.13
Node Name=1016
XS GIS Cut Line= 5
2453870.16304494309077.7662826032454295.67006794309085.085165605
2454343.46721645 309054.830632942454412.68394153309010.953096017
2454604.47227186309057.178069189
#Sta/Elev= 30
       0   412.4   29.46  410.45   78.57  405.36  104.76  403.51  147.31  395.07
   186.6  391.43  199.69  389.66  258.62  378.99  288.08  377.44     435  375.21
  472.71  376.92  475.85  375.91   477.6  374.36     479  373.36  482.14   372.8
  486.46  374.34  491.97  376.71  508.36  377.69  514.92  378.81  531.31  383.75
  537.87  384.43  554.26  388.58  567.32  390.31  583.49  393.45   612.6  401.98
  619.07   402.9  638.47  408.06  664.35  413.26  693.45  417.95  761.37  425.05
#Mann= 3 , 0 , 0
       0      .1       0   477.6    .045       0  486.46      .1       0
Bank Sta=477.6,486.46
XS Rating Curve= 0 ,0
Exp/Cntr=0.3,0.1

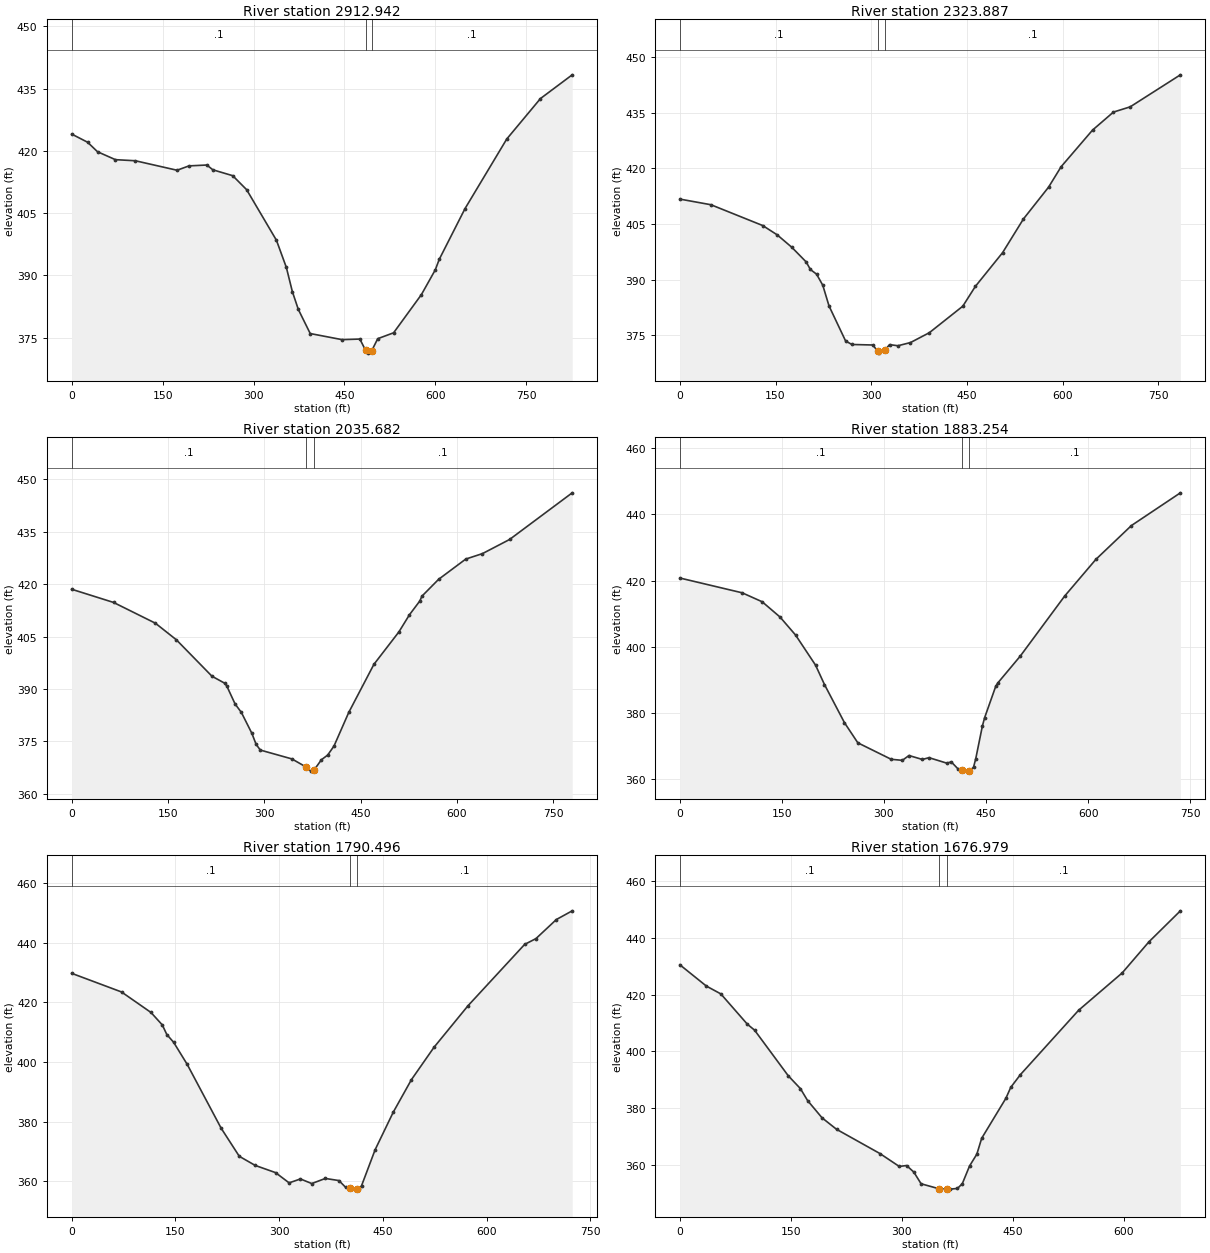
Type RM Length L Ch R = 1 ,2912.942,573.78,589.05,528.46
Node Name=1017
XS GIS Cut Line= 3
2453981.53683794309689.7434051042454325.94362944309444.051967353
 2454653.7841811309210.178419352
#Sta/Elev= 30
       0  424.04   26.24  422.07   42.63  419.78   72.15  417.87  104.95  417.61
  173.82  415.32  193.49  416.37  223.01  416.58  232.85  415.43  265.64  414.01
   288.6  410.64  337.79  398.45  354.19  391.88  364.03  386.08  373.87  381.78
  393.54  375.96  445.98  374.49  475.45  374.63  484.91   371.9  488.54  371.24
  494.79  371.76  504.91  374.72   531.1  376.14  576.94  385.34  599.86  391.31
  606.41  393.85  648.97  406.09  717.73  422.84  773.39   432.6  825.77  438.32
#Mann= 3 , 0 , 0
       0      .1       0  484.91    .045       0  494.79      .1       0
Bank Sta=484.91,494.79
XS Rating Curve= 0 ,0
Exp/Cntr=0.3,0.1

Type RM Length L Ch R = 1 ,2323.887,281.69,288.21,254.7
Node Name=1018
XS GIS Cut Line= 3
2454414.61766469310113.5174919372454553.86016835309901.941471517
2454834.55842586309450.800313443
#Sta/Elev= 30
       0   411.7   48.71  410.18  129.89  404.57  152.62  402.06  175.35  398.73
  198.08  394.75  204.58  392.73  214.32  391.47  224.06  388.47   233.8  382.91
  259.84  373.45  269.68  372.52  302.48  372.38  310.25  370.68  312.32  370.19
  320.79  370.93  328.72  372.48  341.84  372.18  361.52  373.04  391.04  375.69
  443.52  382.84   463.2  388.17  505.83  397.25  538.63  406.36  577.99  414.92
  597.67  420.43  646.87  430.29  679.67  435.15  705.91  436.56  784.62  445.19
#Mann= 3 , 0 , 0
       0      .1       0  310.25    .045       0  320.79      .1       0
Bank Sta=310.25,320.79
XS Rating Curve= 0 ,0
Exp/Cntr=0.3,0.1

Type RM Length L Ch R = 1 ,2035.682,149.63,152.43,150.91
XS GIS Cut Line= 4
2454900.07502711310216.1616436092454801.45744219310010.362842605
2454785.43549261309787.9899277692454879.36181395309473.364244685
#Sta/Elev= 30
       0  418.52    65.2  414.75   130.4  408.81  163.01  404.07  218.43  393.66
  238.04  391.68  241.32  390.94  254.44  385.73  264.27   383.3  280.67   377.3
  287.22  374.17  293.78  372.54  342.96  370.01   365.5  367.65  372.47  366.52
  377.47  366.84  388.86  369.76   398.7  371.12  408.53   373.7  431.48   383.3
  470.66  397.05  509.67  406.35  525.93   411.2  542.18  415.17  545.43  416.54
  571.44  421.36   613.7  427.15  639.71  428.71  681.97  432.75   779.5  446.09
#Mann= 3 , 0 , 0
       0      .1       0   365.5    .045       0  377.47      .1       0
Bank Sta=365.5,377.47
XS Rating Curve= 0 ,0
Exp/Cntr=0.3,0.1

Type RM Length L Ch R = 1 ,1883.254,93.89,92.76,89.99
XS GIS Cut Line= 2
2454921.62157194310221.6862388552454917.33713169309486.022683933
#Sta/Elev= 30
       0  420.75   91.55  416.28  120.98  413.57  147.14  408.97  170.02  403.52
  199.45   394.4  212.53  388.55  241.96     377  261.57  370.92  310.62  365.94
  326.97  365.62  336.78  367.08  356.39  365.89   366.2  366.43  392.36  364.77
   398.9  365.16  408.71  363.06  415.07  362.79  424.97  362.36   431.6  363.52
  434.87  366.09  444.68  376.03  447.95  378.52  464.29  388.02  467.56  389.08
  500.26  397.12  565.65  415.31  611.43  426.38  663.74  436.62  735.68  446.51
#Mann= 3 , 0 , 0
       0      .1       0  415.07    .045       0  424.97      .1       0
Bank Sta=415.07,424.97
XS Rating Curve= 0 ,0
Exp/Cntr=0.3,0.1

Type RM Length L Ch R = 1 ,1790.496,113.25,113.52,114.36
XS GIS Cut Line= 2
2455017.90418777 310227.63832669 2454998.7126251309504.105981097
#Sta/Elev= 30
       0  429.73   72.05  423.48  114.63  416.61     131  412.43  137.55  409.21
  147.38  406.61  167.03   399.2  216.15  377.78  242.35  368.37  265.28  365.32
  294.75   362.9  314.41  359.46  330.78  360.77  347.16  359.23  366.81  360.94
  386.46  360.23  396.28  357.93  402.03  357.72  412.99  357.54  415.93  357.36
  419.21  358.54  438.86  370.61  465.06  383.19  491.26  394.06  524.01  404.95
  573.13  418.87  655.01  439.43  671.39  441.38  700.86  447.77  723.79  450.69
#Mann= 3 , 0 , 0
       0      .1       0  402.03    .045       0  412.99      .1       0
Bank Sta=402.03,412.99
XS Rating Curve= 0 ,0
Exp/Cntr=0.3,0.1

Type RM Length L Ch R = 1 ,1676.979,320.26,335,324.93
Node Name=1019
XS GIS Cut Line= 3
2455110.82985494310207.5514246082455119.68548028309937.159248859
2455099.97981103309531.231254935
#Sta/Elev= 30
       0  430.57   35.85  423.05   55.41  420.29   91.27  409.59  101.04  407.49
  146.68  391.35  162.97  386.87  172.75  382.63  192.31  376.53  211.87  372.49
  270.54  363.93  296.76  359.36  306.59   359.7  316.42  357.38  326.25  353.25
  350.98  351.45  361.01  351.38  365.58  351.36  375.42   351.6  381.97  353.27
   391.8  359.54  401.64   363.7  408.19  369.31  440.97  383.45  447.52   387.3
  460.63   391.8  539.29  414.51  598.28  427.71  634.34  438.66  676.94  449.62
#Mann= 3 , 0 , 0
       0      .1       0  350.98    .045       0  361.01      .1       0
Bank Sta=350.98,361.01
XS Rating Curve= 0 ,0
Exp/Cntr=0.3,0.1

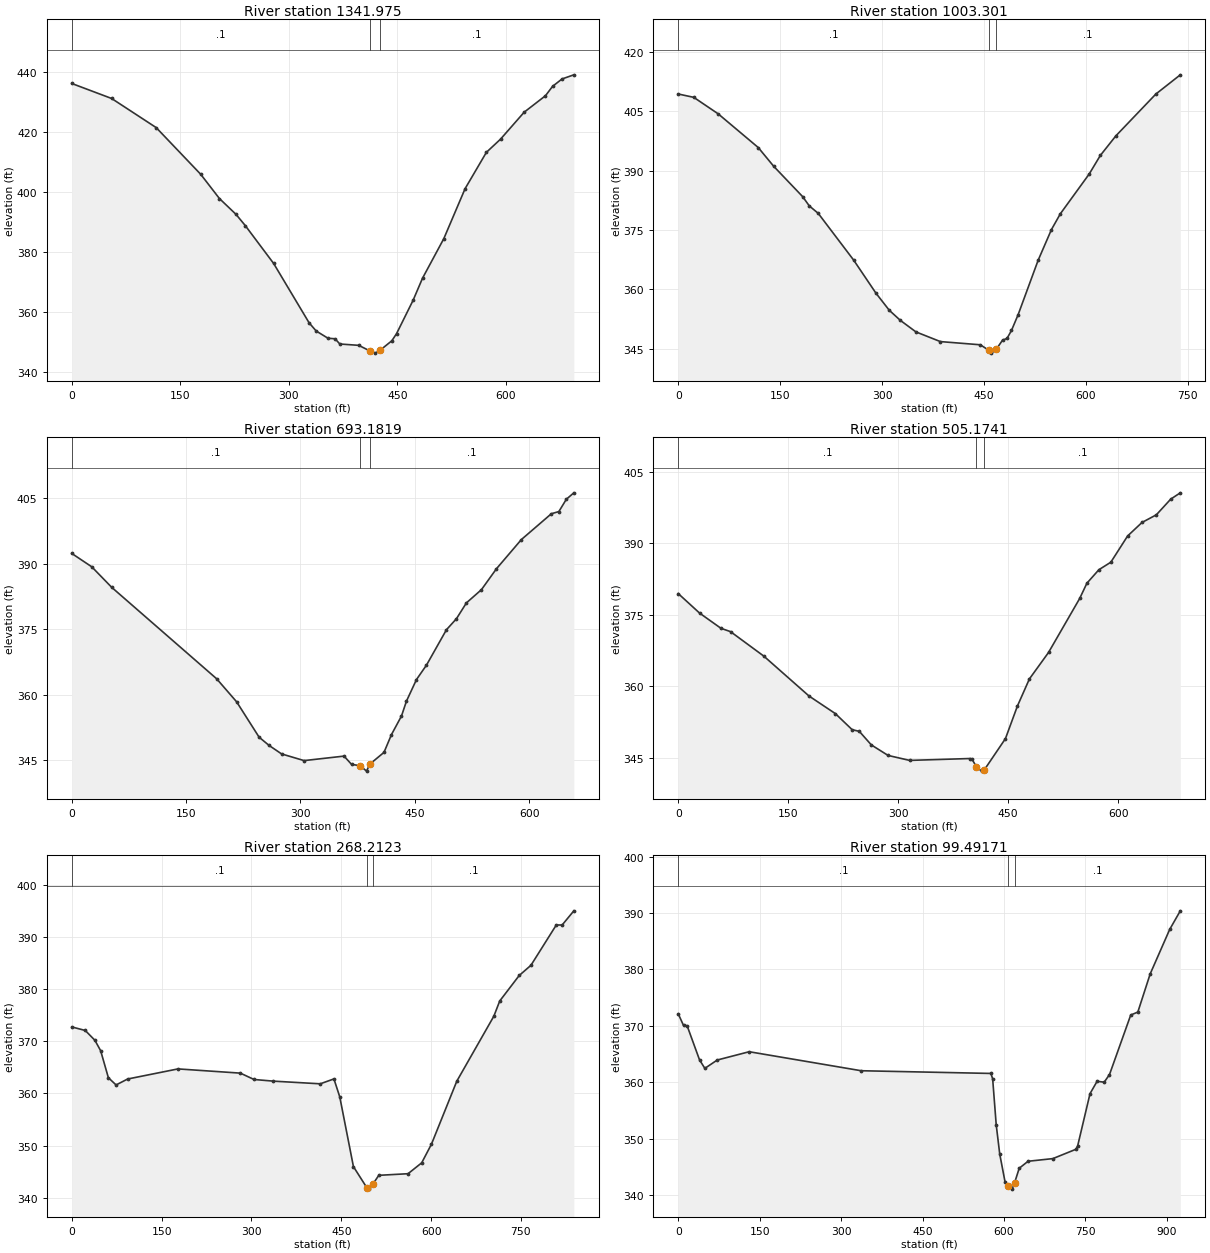
Type RM Length L Ch R = 1 ,1341.975,339.23,338.67,331.67
Node Name=1020
XS GIS Cut Line= 3
2455474.07125445310154.8107164352455442.55852219309913.736723527
2455341.71686035309474.131303519
#Sta/Elev= 30
       0  436.24   55.11  431.23   116.7  421.51  178.29  405.91  204.22   397.8
  226.92  392.58  239.88  388.79  279.08  376.15   328.1  356.33  337.91  353.59
  354.25  351.17  364.05  350.99  370.59  349.25  396.73   348.8  412.97  346.84
  419.61   346.2  425.83  347.08  442.49  350.32  449.03   352.7  471.91  363.85
  484.98  371.24  514.39  384.44  543.81  401.13  573.22  413.24  592.83  417.66
  625.51  426.66  654.93  432.15  664.73  435.28  677.81  437.75  694.15  439.13
#Mann= 3 , 0 , 0
       0      .1       0  412.97    .045       0  425.83      .1       0
Bank Sta=412.97,425.83
XS Rating Curve= 0 ,0
Exp/Cntr=0.3,0.1

Type RM Length L Ch R = 1 ,1003.301,290.04,310.12,286.08
XS GIS Cut Line= 2
2455742.60615045310115.3340893542455679.07117252309379.155115515
#Sta/Elev= 30
       0  409.41   22.89  408.56   58.85  404.38   117.7  395.87  140.59   391.1
  183.09  383.44   192.9  381.09  205.98  379.22  258.29  367.35  290.99  359.01
  310.61  354.68  326.95  352.12  349.84  349.21  385.81  346.76  444.66  345.95
  456.75  344.59     461  343.84  467.85  344.77  477.35  347.13  483.89  347.56
  490.43  349.57  500.24  353.57  529.67  367.33  549.28  375.11  562.36   379.1
  604.86  389.17  621.21  393.86   644.1  398.82  702.95   409.4  738.92  414.26
#Mann= 3 , 0 , 0
       0      .1       0  456.75    .045       0  467.85      .1       0
Bank Sta=456.75,467.85
XS Rating Curve= 0 ,0
Exp/Cntr=0.3,0.1

Type RM Length L Ch R = 1 ,693.1819,181.17,188.01,173.5
Node Name=1021
XS GIS Cut Line= 2
 2455947.7441916 310047.93527402 2455952.4708882309389.314872101
#Sta/Elev= 30
       0  392.38   26.21  389.32   52.43  384.61  190.05  363.68  216.27   358.4
  245.76   350.3  258.87  348.41  275.25  346.47  304.74  344.94  357.17  345.97
     367  344.08  378.46  343.77  386.66  342.53  391.13  344.15   409.6  346.83
  419.43  350.91  432.54  355.15  439.09  358.57   452.2   363.5  465.31   366.8
  491.52  374.91  504.63  377.43  517.73  381.06   537.4  384.08  557.06  388.86
  589.82  395.56  629.15  401.47  638.98  401.97  648.81  404.79  658.64  406.26
#Mann= 3 , 0 , 0
       0      .1       0  378.46    .045       0  391.13      .1       0
Bank Sta=378.46,391.13
XS Rating Curve= 0 ,0
Exp/Cntr=0.3,0.1

Type RM Length L Ch R = 1 ,505.1741,241.88,236.96,215.74
XS GIS Cut Line= 3
2456029.89560211310033.8434386852456115.52994527309904.010693103
2456100.33673419309375.011423022
#Sta/Elev= 30
       0  379.49   29.16  375.39   58.32   372.2   71.28  371.51  116.65  366.38
   178.4     358  214.33  354.31   237.2  350.94     247  350.59  263.33  347.75
   286.2  345.54   315.6   344.5  397.27  344.89  400.54  344.78   406.5   343.2
  413.61  342.25  417.31  342.49  446.27  349.07  462.61  355.91  478.94  361.59
  505.08  367.15  547.54  378.47  557.34  381.66  573.68  384.49  590.01  386.07
  612.88  391.57  632.48   394.4  652.08  396.01  671.68   399.3  684.75  400.62
#Mann= 3 , 0 , 0
       0      .1       0   406.5    .045       0  417.31      .1       0
Bank Sta=406.5,417.31
XS Rating Curve= 0 ,0
Exp/Cntr=0.3,0.1

Type RM Length L Ch R = 1 ,268.2123,147.01,168.72,182.37
XS GIS Cut Line= 4
2456072.98901986310040.1967724412456179.34116936309951.799967602
2456345.08526044309714.2338416872456173.81657411309341.310374931
#Sta/Elev= 30
       0  372.78   22.51   372.1   38.59  370.22   48.24  368.21   61.11  363.03
   73.97  361.64   93.27  362.78  177.35  364.72   281.5  363.91  304.28  362.69
  336.83  362.37  414.94  361.86  437.73   362.8   447.5  359.34   470.3  345.96
  492.59  341.93  496.36  341.64   503.3  342.69  512.64  344.29   561.5   344.6
  584.29  346.69  600.58  350.27  642.92  362.37   704.8  374.85  714.57  377.76
  747.14  382.66  766.68  384.61  809.02  392.35  818.79  392.35  838.33  395.07
#Mann= 3 , 0 , 0
       0      .1       0  492.59    .045       0   503.3      .1       0
Bank Sta=492.59,503.3
XS Rating Curve= 0 ,0
Exp/Cntr=0.3,0.1

Type RM Length L Ch R = 1 ,99.49171,90.79,99.49,105.18
XS GIS Cut Line= 4
2456085.41976927310051.246291026 2456184.8660927309961.468583435
2456429.33837278309605.1192305242456455.58110245309247.388646767
#Sta/Elev= 30
       0  372.13     9.8  370.06   16.34  370.02   39.21  363.97   49.02  362.46
   71.89  363.94  130.71  365.41  336.95  362.04  575.91  361.56  579.17  360.61
  585.69  352.48  592.21  347.26  601.99  342.33  607.94  341.67  615.04  341.05
  619.62  342.19  628.08  344.75  644.38  345.99  690.04  346.46  732.43  348.11
  735.69   348.7  758.51  357.98  771.56  360.17   784.6  360.01  794.38  361.36
  833.51  371.92  846.56  372.44  869.38  379.22  905.25  387.09  924.82  390.39
#Mann= 3 , 0 , 0
       0      .1       0  607.94    .045       0  619.62      .1       0
Bank Sta=607.94,619.62
XS Rating Curve= 0 ,0
Exp/Cntr=0.3,0.1

Chan Stop Cuts=-1
Use User Specified Reach Order=0
Composite Channel Slope=5